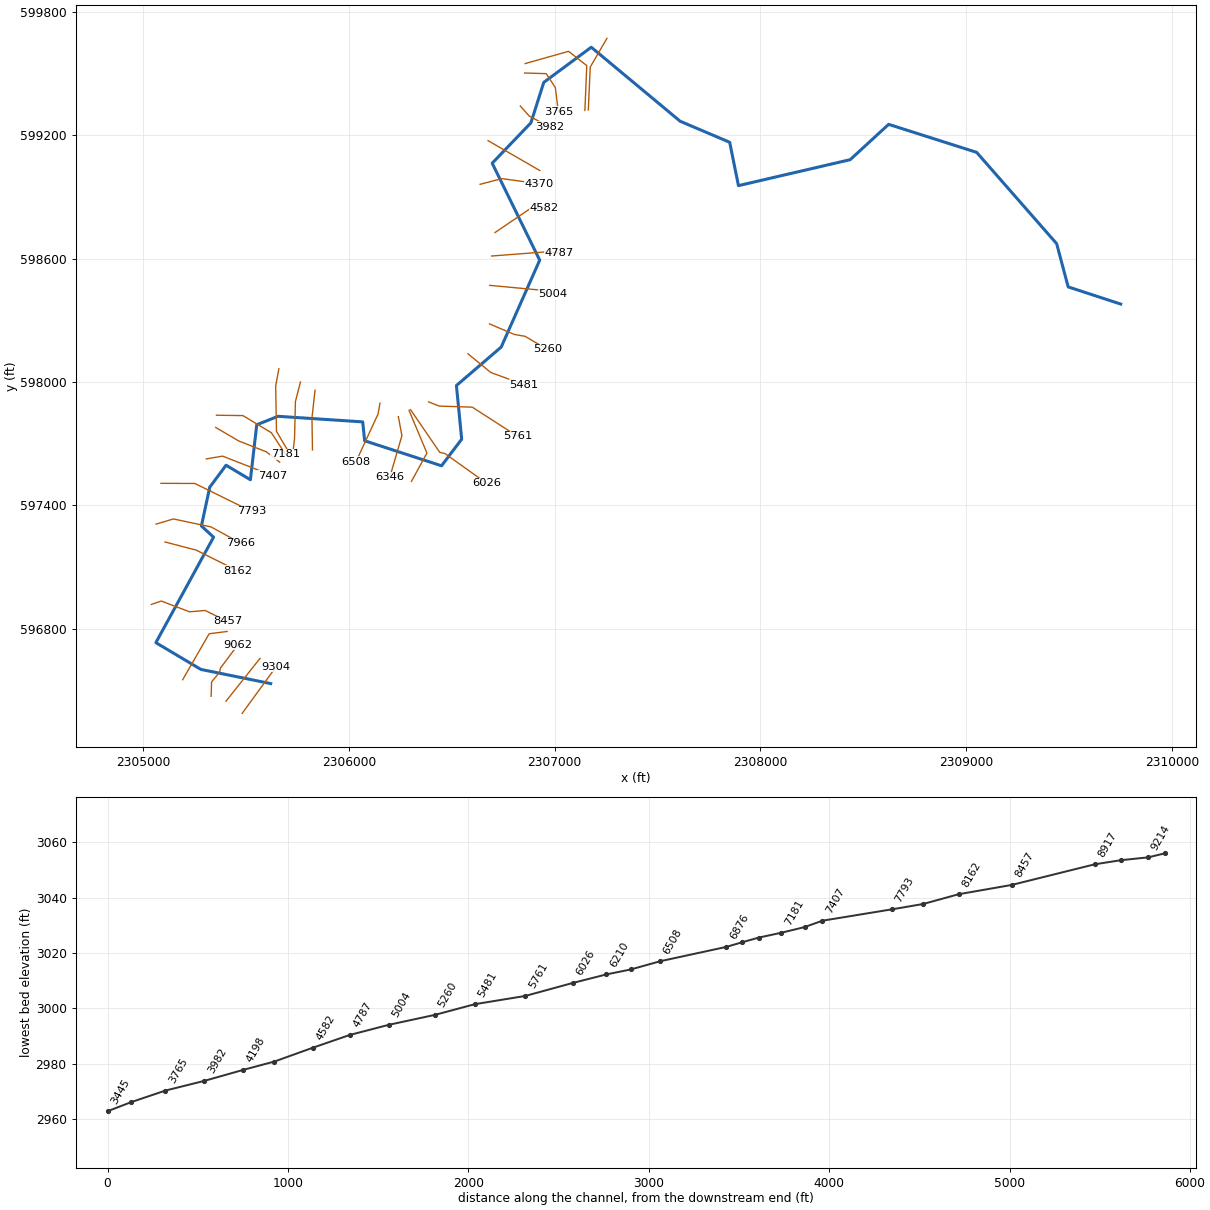
--- OLDRDRN.prj (project) ---

Proj Title=OLDRDRN
Current Plan=p01
Default Exp/Contr=0,0
English Units
Geom File=g01
Flow File=f01
Plan File=p01
Background Map Layer=Inundation Boundary (01pct Value_0)
BEGIN DESCRIPTION:
----------MODEL BY WOOD PLC 2021----------
Stream Name: Old Road Run
Flood Zone: Enhanced Approximate
Pocahontas County, WV
HEC-RAS Version: RAS 6.1
Vertical Datum: NAVD88
Projection: NAD 1983 StatePlane West Virginia S FIPS 4702 (US Feet)
Terrain: 1-meter LIDAR (FEMA Region III 3DEP collected 2016-2018)
Land Use: 2019 NLCD
Hydrologic Method:
WV SIR2010-5033 regression equations
END DESCRIPTION:
DSS Export Rating Curves= 0
DSS Export Rating Curve Sorted= 0
DSS Export Volume Flow Curves= 0
DXF OffsetX= 0
DXF OffsetY= 0
DXF ScaleX= 0
DXF ScaleY= 0

--- OLDRDRN.p01 (plan) ---

Plan Title=Floodplain
Program Version=6.10
Short Identifier=Floodplain
Geom File=g01
Flow File=f01
Subcritical Flow
K Sum by GR= 0
Std Step Tol= 0.01
Critical Tol= 0.01
Num of Std Step Trials= 20
Max Error Tol= 0.3
Flow Tol Ratio= 0.001
Split Flow NTrial= 30
Split Flow Tol= 0.02
Split Flow Ratio= 0.02
Log Output Level= 0
Friction Slope Method= 1
Unsteady Friction Slope Method= 2
Unsteady Bridges Friction Slope Method= 1
Parabolic Critical Depth
Global Vel Dist= 0 , 0 , 0
Global Log Level= 0
CheckData=True
Encroach Param=-1 ,0,0, 0
Mapping Interval=1HOUR
Computation Time Step Use Courant=        0
Computation Time Step Use Time Series=    0
Computation Time Step Count To Double=0
Computation Time Step Max Doubling=0
Computation Time Step Max Halving=0
Computation Time Step Residence Courant=0
Run HTab= 0
Run UNet= 0
Run Sediment= 0
Run PostProcess= 0
Run WQNet= 0
Run RASMapper=-1
UNET Theta= 0
UNET Theta Warmup= 0
UNET ZTol= 0
UNET ZSATol= 0
UNET MxIter= 0
UNET Max Iter WO Improvement= 0
UNET MaxInSteps= 0
UNET DtIC= 0
UNET DtMin= 0
UNET MaxCRTS= 0
UNET WFStab= 0
UNET SFStab= 0
UNET WFX= 1
UNET SFX= 1
UNET Gravity=32.174
UNET 1D Methodology=Finite Difference
UNET DSS MLevel= 1
UNET Pardiso=0
UNET DZMax Abort= 0
UNET Use Existing IB Tables= 0
UNET Froude Reduction=False
UNET Froude Limit= 0
UNET Froude Power= 0
UNET D1 Cores= 0
UNET WindReference=Eulerian
UNET WindDragFormulation=Hsu (1988)
UNET D2 Coriolis=0
UNET D2 Cores= 0
UNET D2 Theta= 1
UNET D2 Theta Warmup= 1
UNET D2 Z Tol= 0.01
UNET D2 Volume Tol= 0.01
UNET D2 Max Iterations= 20
UNET D2 Equation= 0
UNET D2 RampUpFraction=0.1
UNET D2 TimeSlices= 1
UNET D2 Turbulence Formulation=Non-Conservative (original)
UNET D2 Eddy Viscosity=0.3
UNET D2 Transverse Eddy Viscosity=0.1
UNET D2 Smagorinsky Mixing=0
UNET D2 BCVolumeCheck=0
UNET D2 Cores=0
UNET D2 SolverType=PARDISO (Direct)
UNET D2 Minimum Iterations= 2147483647
UNET D2 Maximum Iterations= 2147483647
UNET D2 Restart Number= 10
UNET D2 Relaxation Coeff=1.3
UNET D2 SOR Precondition Iterations= 10
UNET D2 ILUT Maximum Fill= 8
UNET D2 ILUT Tolerance=1E-08
UNET D1D2 MaxIter= 0
UNET D1D2 ZTol=0.01
UNET D1D2 QTol=0.1
UNET D1D2 MinQTol=1
Write IC File= 0
Write IC File at Fixed DateTime=0
Write IC File at Sim End=0
Echo Input=False
Echo Parameters=False
Echo Output=False
Write Detailed= 0
HDF Write Warmup=0
HDF Write Time Slices=0
HDF Flush=0
HDF Compression= 1
HDF Chunk Size= 1
HDF Spatial Parts= 1
HDF Use Max Rows=0
HDF Fixed Rows= 1
Calibration Method= 0
Calibration Iterations= 20
Calibration Max Change=0.05
Calibration Tolerance=0.2
Calibration Maximum=1.5
Calibration Minimum=0.5
Calibration Optimization Method= 1
WQ AD Non Conservative
WQ ULTIMATE=-1
WQ Max Comp Step=1HOUR
WQ Output Interval=15MIN
WQ Output Selected Increments= 0
WQ Output face flow=0
WQ Output face velocity=0
WQ Output face area=0
WQ Output face dispersion=0
WQ Output cell volume=0
WQ Output cell surface area=0
WQ Output cell continuity=0
WQ Output cumulative cell continuity=0
WQ Output face conc=0
WQ Output face dconc_dx=0
WQ Output face courant=0
WQ Output face peclet=0
WQ Output face adv mass=0
WQ Output face disp mass=0
WQ Output cell mass=0
WQ Output cell source sink temp=0
WQ Output nsm pathways=0
WQ Output nsm derived pathways=0
WQ Create Restart=0
WQ Fixed Restart=0
WQ System Summary=0
WQ Write To DSS=0
Sorting and Armoring Iterations= 10
XS Update Threshold= 0.02
Bed Roughness Predictor= 0
Hydraulics Update Threshold= 0.02
Energy Slope Method= 1
Volume Change Method= 1
Sediment Retention Method= 0
Sediment TS Multiplier= 1
Warm Up Method= 0
XS Weighting Method= 0
Number of US Weighted Cross Sections= 1
Number of DS Weighted Cross Sections= 1
Upstream XS Weight=0
Main XS Weight=1
Downstream XS Weight=0
Number of DS XS's Weighted with US Boundary= 1
Upstream Boundary Weight= 1
Weight of XSs Associated with US Boundary= 0
Number of US XS's Weighted with DS Boundary= 1
Downstream Boundary Weight= 0.5
Weight of XSs Associated with DS Boundary= 0.5
Percentile Method= 0
Sediment Output Level= 3
Mass or Volume Output= 0
Output Increment Type= 1
Profile and TS Output Increment= 1
Transport Output Increment 1
XS Output Flag= 0
XS Output Increment= 10
Read HDF5 Sediment Hotstart= 0
Sediment Hotstart Type= 0
Write Gradation File= 0
Read Gradation Hotstart= 0
Write HDF5 File= 1
Write Binary Output= 1
Write DSS Sediment File= 0
DSS Sediment Output Type= 1
SV Curve= 0
Specific Gage Flag= 0
Subcell Erosion Methods= 0
Subcell Deposition Methods= 0
Advection Scheme= 1
Matrix Solver= 0
Implicit Weighting Factor= 1
Maximum Outer Loop Convergence Iterations= 5
Convergence Maximum Absolute= 0.001
Convergence RMSE= 0.0001
Grain Fractions Max Abs Error= 0.001
Max Subgrid Regions= 1
Max Subgrid Length Scale= 3.402823E+38
Initial Layer Thickness= 3.402823E+38
Min Layer Thickness= 3.402823E+38
Max Layer Thickness= 3.402823E+38
Number of Layers= 5

--- OLDRDRN.f01 (steady flow) ---

Flow Title=USGS Regression Equation
Program Version=6.10
Number of Profiles= 6
Profile Names=01pct,10pct,04pct,02pct,0_2pct,01plus
River Rch & RM=OLDRDRN,Main            ,9304
     618     328     435     524     862     914
River Rch & RM=OLDRDRN,Main            ,3445
     900     484     639     765    1250    1330
Boundary for River Rch & Prof#=OLDRDRN,Main            , 1
Up Type= 0
Dn Type= 3
Dn Slope=0.00117
Boundary for River Rch & Prof#=OLDRDRN,Main            , 2
Up Type= 0
Dn Type= 3
Dn Slope=0.00117
Boundary for River Rch & Prof#=OLDRDRN,Main            , 3
Up Type= 0
Dn Type= 3
Dn Slope=0.00117
Boundary for River Rch & Prof#=OLDRDRN,Main            , 4
Up Type= 0
Dn Type= 3
Dn Slope=0.00117
Boundary for River Rch & Prof#=OLDRDRN,Main            , 5
Up Type= 0
Dn Type= 3
Dn Slope=0.00117
Boundary for River Rch & Prof#=OLDRDRN,Main            , 6
Up Type= 0
Dn Type= 3
Dn Slope=0.00117
DSS Import GetInterval= 0
DSS Import GetPeak= 0
DSS Import FillOption= 0

--- OLDRDRN.g01 (geometry) ---

Geom Title=Geometry
Program Version=6.10

River Reach=OLDRDRN         ,Main
Reach XY= 30
2305620.15600003596533.3499999942305280.68494577596602.335728724
2305062.04900001596732.4640000162305342.48800002597245.570999995
2305283.40700002597299.9660000212305323.79900002597488.531000003
2305403.23044885597595.6378372422305521.54400004597524.901999995
2305552.33800001597792.4029999972305655.87406412597833.611116975
     2306067.388597806.4000000062306076.63300003597714.605000019
2306450.47400001      597592.8312306548.38900003597722.406000003
2306522.82899998597983.2370000032306740.51978249598170.526431479
2306927.59300002598593.135000005     2306696.676599064.724000022
2306884.87400003599261.3240000162306947.38632231599458.029927048
2307178.21499999599628.9889999932307610.14600001 599269.01000002
2307850.96600004599166.5820000022307893.54000004598955.697999999
2308436.54390927599081.9668362952308623.49600001599253.821999997
     2309051.109599117.6490000192309440.06000003598673.312000036
2309495.98600003598463.1380000112309751.43290089598379.519838065

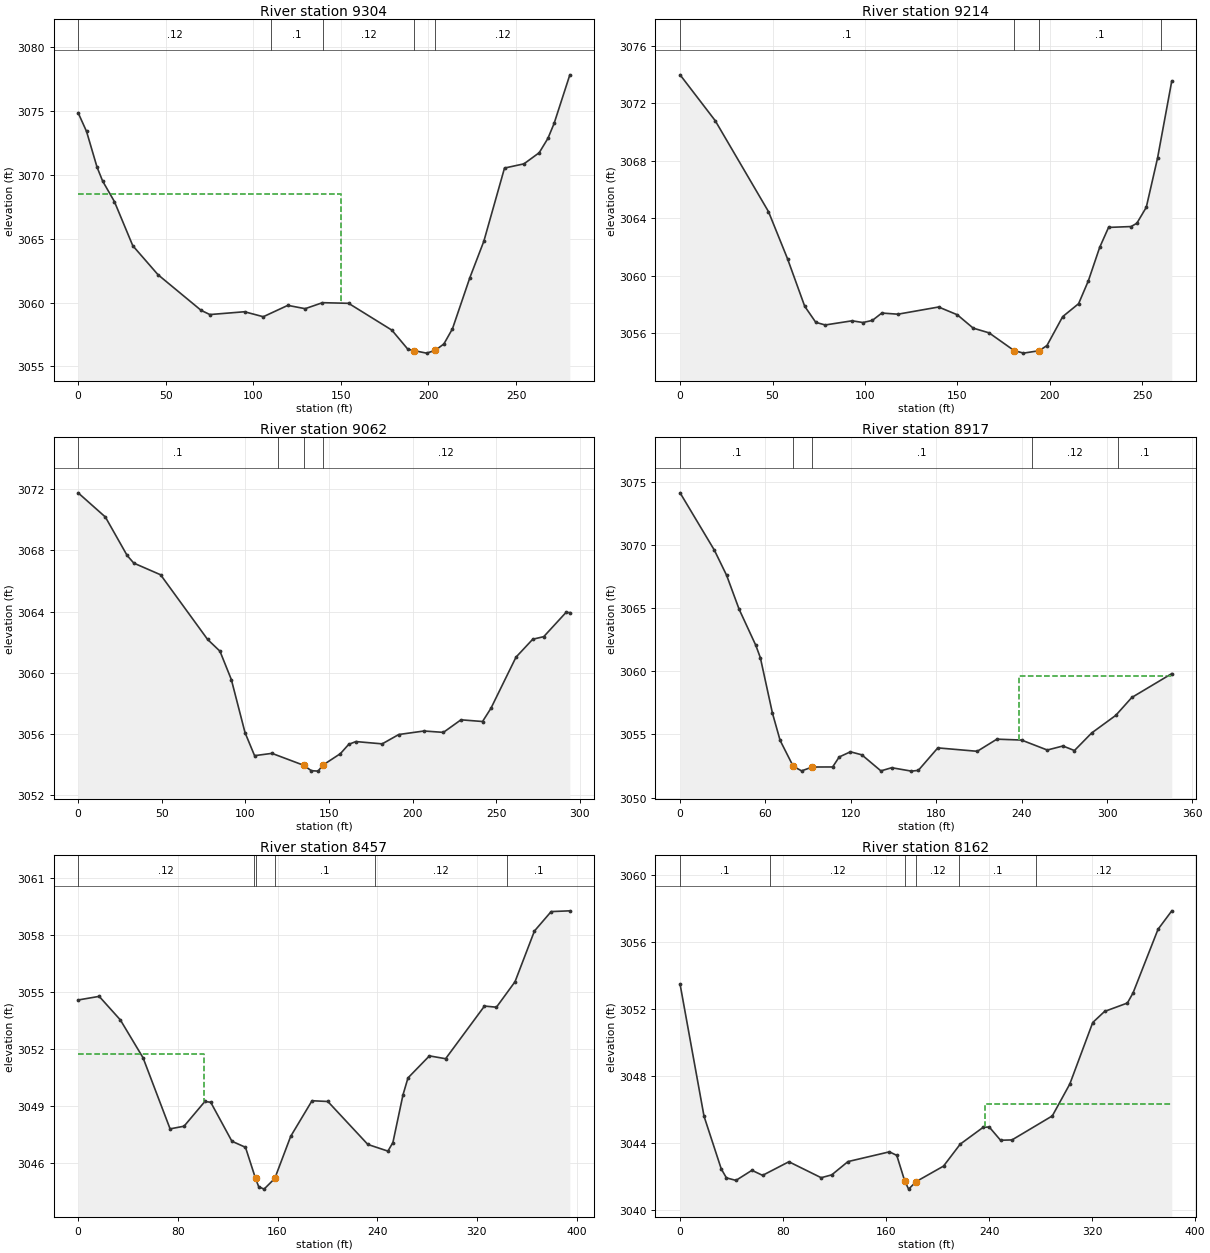
Type RM Length L Ch R = 1 ,9304    ,90.9,90.6,90
XS GIS Cut Line= 2
 2305481.3310347596388.4199881972305646.59806577596615.272375182
#Sta/Elev= 30
       0 3074.86     4.8  3073.4    10.8  3070.6      14 3069.51    20.7 3067.91
    31.2 3064.45    45.6 3062.18    70.2 3059.39    75.2 3059.06      95 3059.28
   105.7 3058.89   119.7 3059.78   129.6 3059.52   139.5 3059.99   154.4 3059.94
   179.1 3057.84   188.2 3056.35   191.5 3056.24   198.9 3056.04   203.8 3056.25
   208.8 3056.76   213.7 3057.95   223.6 3061.94   231.6  3064.8   243.4 3070.53
   254.5 3070.86   263.2 3071.73   268.2 3072.86   271.7 3074.02   280.7 3077.83
#Mann= 5 ,-1,0
       0     .12       0     110      .1       0     140     .12       0
   191.5    .045       0   203.8     .12       0
#XS Ineff= 2 , 0
             150  3068.5
Permanent Ineff=
       F       F
Bank Sta=191.5,203.8
XS Rating Curve= 0 ,0
Exp/Cntr(USF)=0,0
Exp/Cntr=0.3,0.1

Type RM Length L Ch R = 1 ,9214    ,142.9,152.3,154.2
XS GIS Cut Line= 2
2305402.92727415596447.6989472052305568.24537497596656.007570695
#Sta/Elev= 30
       0 3073.99      19  3070.8    47.8 3064.47    58.1 3061.19    67.4 3057.88
    73.4 3056.76    78.5 3056.58      93 3056.87    98.9 3056.75     104  3056.9
   109.1 3057.41   117.8 3057.33   139.8 3057.83   149.9 3057.29   158.5 3056.36
   167.1 3056.03   180.6  3054.8   185.7 3054.62  194.25 3054.79   198.4 3055.15
   206.9 3057.16   215.5 3058.06   220.8 3059.66   226.9 3061.98   231.7 3063.37
   243.9 3063.43     247 3063.66   252.1 3064.77   258.2  3068.2   265.9 3073.57
#Mann= 4 ,-1,0
       0      .1       0   180.6    .045       0  194.25      .1       0
     260     .12       0
Bank Sta=180.6,194.25
XS Rating Curve= 0 ,0
Exp/Cntr(USF)=0,0
Exp/Cntr=0.3,0.1

Type RM Length L Ch R = 1 ,9062    ,147.7,144.3,140.7
XS GIS Cut Line= 5
2305330.67504818596471.935272032 2305332.8705204596541.380013333
2305371.66143948596588.3952032212305375.56966881596608.327172823
2305461.54043927596722.912811036
#Sta/Elev= 30
       0 3071.75    16.3 3070.17    29.3 3067.66    33.3 3067.16    49.3  3066.4
    77.4 3062.18    84.8 3061.41    91.6 3059.56    99.8 3056.09   105.5 3054.59
   115.9 3054.74   134.9 3053.96   139.4 3053.61   143.5 3053.58  146.16 3053.96
   156.8 3054.72   161.8 3055.33   166.1 3055.51   181.8 3055.36   191.7 3055.97
   206.8  3056.2   218.4 3056.11   228.9 3056.93   241.8 3056.82   246.8 3057.68
   261.8 3061.02   271.8 3062.19   278.4 3062.36   291.7 3063.94     294 3063.93
#Mann= 4 ,-1,0
       0      .1       0  119.48     .12       0   134.9    .045       0
  146.16     .12       0
Bank Sta=134.9,146.16
XS Rating Curve= 0 ,0
Exp/Cntr(USF)=0,0
Exp/Cntr=0.3,0.1

Type RM Length L Ch R = 1 ,8917    ,474.9,460.1,441.3
XS GIS Cut Line= 4
2305192.41247146 596552.289234312305310.69306187596757.621533373
2305321.17942376596775.8331588832305407.96695263596786.869304624
#Sta/Elev= 30
       0 3074.13    24.1 3069.59    32.7  3067.6    41.5 3064.91    53.2 3062.06
    56.4 3061.08    64.9 3056.69    70.3 3054.53    79.5 3052.48    85.4 3052.12
    92.93052.425   107.2 3052.43   111.8 3053.22   119.7 3053.63   127.7 3053.39
   141.1 3052.12   148.7 3052.37   162.6  3052.1   167.4 3052.16   181.1 3053.94
   208.8 3053.67   222.6 3054.63   239.9 3054.56     258 3053.77     269 3054.09
   277.1 3053.73   289.2 3055.12   306.1 3056.51   317.4 3057.93   345.5 3059.82
#Mann= 5 ,-1,0
       0      .1       0    79.5    .045       0    92.9      .1       0
  246.96     .12       0  307.98      .1       0
#XS Ineff= 2 , 0
                           238.2         3059.64
Permanent Ineff=
       F       F
Bank Sta=79.5,92.9
XS Rating Curve= 0 ,0
Exp/Cntr(USF)=0,0
Exp/Cntr=0.3,0.1

Type RM Length L Ch R = 1 ,8457    ,295.4,294.8,293.9
XS GIS Cut Line= 5
2305040.15067803596918.4224672832305088.22099383596934.908608863
2305225.82211807596882.489132964 2305301.4729526596889.041567452
2305409.67157067596835.696339199
#Sta/Elev= 30
       0 3054.59    16.9 3054.78    33.9 3053.54    52.1 3051.55    73.8 3047.81
      85 3047.95   101.7 3049.25   106.4 3049.21   123.4 3047.16   134.3 3046.84
  142.37  3045.2   144.9 3044.77   149.2 3044.64   157.8  3045.2   170.6 3047.42
   187.7 3049.29   200.4 3049.25   232.5 3046.99   248.6 3046.64   252.6 3047.09
   260.7  3049.6   264.7 3050.49   281.9 3051.65   294.9  3051.5   326.1 3054.27
   335.7 3054.21   350.6 3055.55   366.2 3058.22   379.6 3059.24   394.6 3059.28
#Mann= 6 ,-1,0
       0     .12       0  140.82      .1       0  142.37    .045       0
   157.8      .1       0  238.07     .12       0     344      .1       0
#XS Ineff= 2 , 0
          100.73 3051.76
Permanent Ineff=
       F       F
Bank Sta=142.37,157.8
XS Rating Curve= 0 ,0
Exp/Cntr(USF)=0,0
Exp/Cntr=0.3,0.1

Type RM Length L Ch R = 1 ,8162    ,193.7,195.9,197
XS GIS Cut Line= 3
2305106.16546384597222.2717094232305257.53444224597182.773270166
2305459.10872078597081.786980176
#Sta/Elev= 30
       0 3053.47    18.6 3045.61      32 3042.47      36 3041.94    43.4 3041.79
    55.8 3042.39    64.1 3042.09    84.5  3042.9   109.6 3041.95   117.8 3042.12
   130.4 3042.91   162.6 3043.49   168.3 3043.28   174.5 3041.75   177.5 3041.27
   183.4 3041.72   204.6 3042.64   217.6 3043.95   235.4 3044.95   240.1 3044.97
   248.9 3044.18   257.8  3044.2   289.1 3045.63   302.7 3047.53   320.5 3051.19
   329.7 3051.85   347.4 3052.35   351.8 3052.95   371.2 3056.74   381.9 3057.84
#Mann= 6 ,-1,0
       0      .1       0      70     .12       0   174.5    .045       0
   183.4     .12       0  216.44      .1       0  276.44     .12       0
#XS Ineff= 2 , 0
                          236.88         3046.33
Permanent Ineff=
       F       F
Bank Sta=174.5,183.4
XS Rating Curve= 0 ,0
Exp/Cntr(USF)=0,0
Exp/Cntr=0.3,0.1

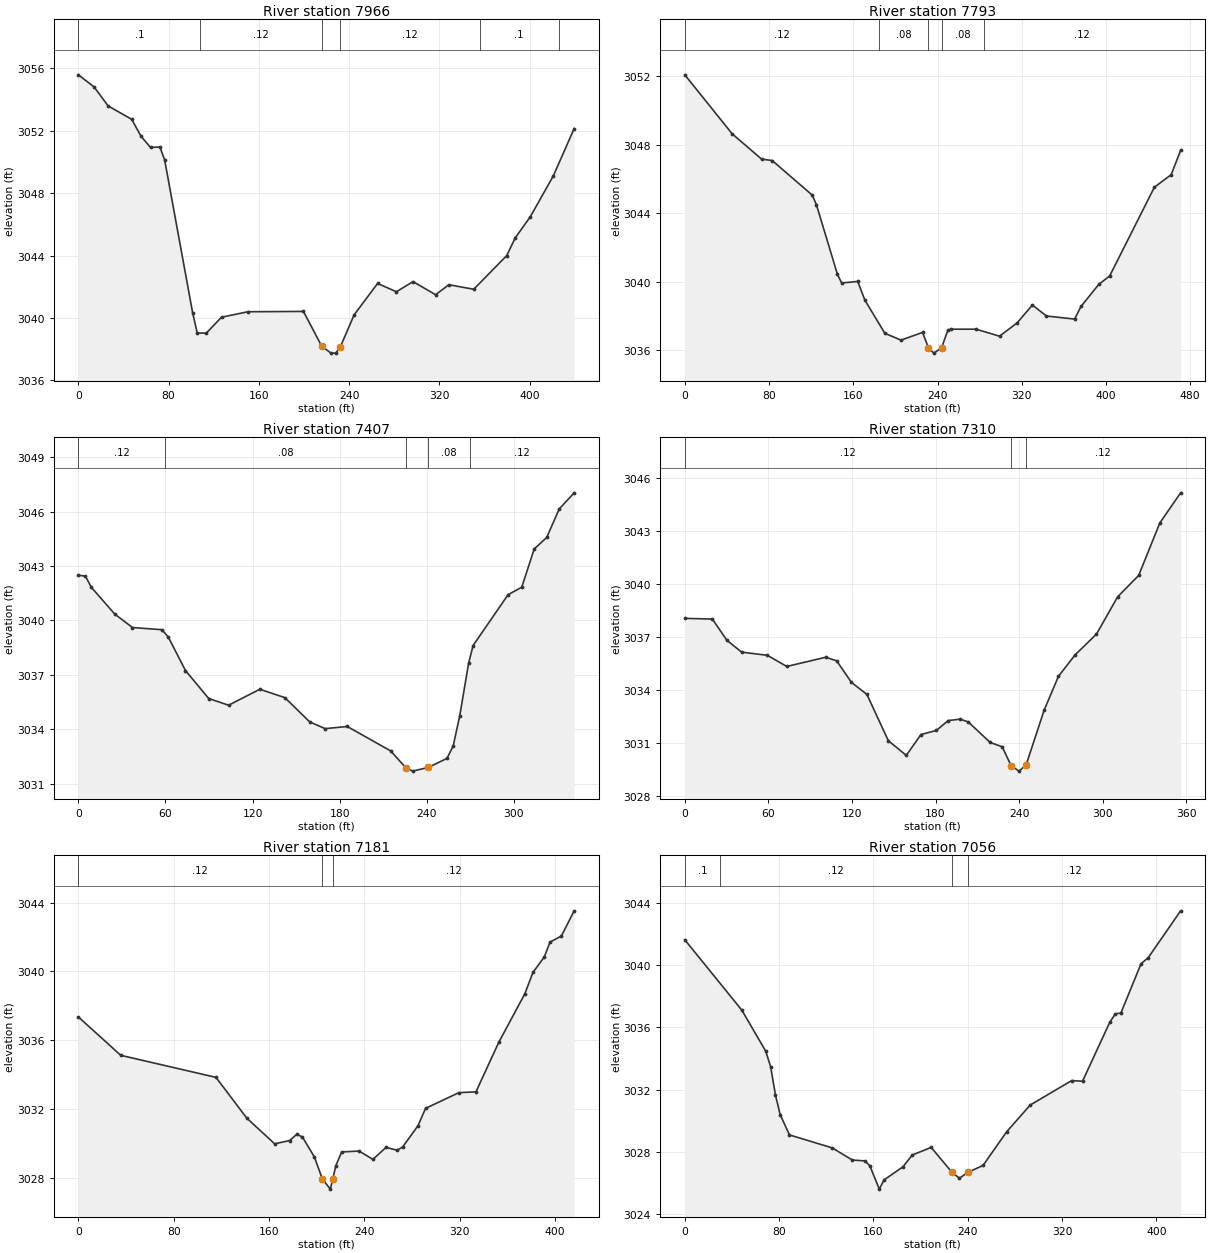
Type RM Length L Ch R = 1 ,7966    ,175.9,173.1,170.5
XS GIS Cut Line= 4
 2305062.9026361 597308.898810062305147.33771492597334.320124112
2305330.73433772597295.280248961 2305474.1831813597216.292594585
#Sta/Elev= 30
       0 3055.57    13.9  3054.8    26.4 3053.58    47.3 3052.72    55.6 3051.63
      64 3050.92    72.3 3050.95    76.5 3050.12   101.3 3040.33   105.4 3039.04
   113.4 3039.03   126.9 3040.05   150.4  3040.4   199.5 3040.42   215.8 3038.18
     224 3037.75   228.1 3037.75   232.2 3038.15   244.4  3040.2   265.2 3042.21
   281.9 3041.68   296.6 3042.33   316.6 3041.49   328.4 3042.13   350.4 3041.84
   379.6 3043.99   387.2 3045.13   400.6 3046.49     421 3049.11   439.4 3052.13
#Mann= 6 ,-1,0
       0      .1       0  108.18     .12       0   215.8    .045       0
   232.2     .12       0  355.68      .1       0  425.68     .12       0
Bank Sta=215.8,232.2
XS Rating Curve= 0 ,0
Exp/Cntr(USF)=0,0
Exp/Cntr=0.3,0.1

Type RM Length L Ch R = 1 ,7793    ,378.7,386.1,385.2
XS GIS Cut Line= 3
2305087.12887496597507.5016493332305251.33591304597506.856020565
2305526.48722819597371.410489639
#Sta/Elev= 30
       0 3052.09      45 3048.64      73 3047.16      83 3047.08     121 3045.06
     125  3044.5     145 3040.42     149 3039.92   164.2 3040.01   171.1 3038.91
     190 3036.98   205.3 3036.58   225.8 3037.03   231.4 3036.13   236.5 3035.82
   243.8 3036.12   249.9 3037.17   252.7 3037.22   276.6 3037.22   298.9 3036.81
   315.5 3037.58   330.1 3038.63   343.5 3037.99   370.2 3037.81   376.3 3038.55
   393.2 3039.84   403.5 3040.33     446 3045.52   461.9 3046.25   470.9 3047.67
#Mann= 5 ,-1,0
       0     .12       0  184.21     .08       0   231.4    .045       0
   243.8     .08       0  284.21     .12       0
Bank Sta=231.4,243.8
XS Rating Curve= 0 ,0
Exp/Cntr(USF)=0,0
Exp/Cntr=0.3,0.1

Type RM Length L Ch R = 1 ,7407    ,97.3,97.1,97
XS GIS Cut Line= 3
2305307.38443893597626.4069193772305386.30300722597639.880821281
2305629.79566306597544.601086388
#Sta/Elev= 30
       0 3042.49     4.9 3042.44     8.9 3041.83    25.1 3040.35    37.3 3039.61
    57.6 3039.49      62 3039.08    73.8 3037.24    89.8  3035.7   103.5 3035.33
     125 3036.21   142.2 3035.75   159.4 3034.41     170 3034.04   185.2 3034.16
   215.2 3032.81   225.6 3031.88   230.2  3031.7   240.9  3031.9   253.9  3032.4
   258.2 3033.09   262.7 3034.75   268.8 3037.64   271.9 3038.62     296 3041.42
   305.4 3041.83     314 3043.94   322.6 3044.57   331.2 3046.14   341.5 3047.03
#Mann= 5 ,-1,0
       0     .12       0      60     .08       0   225.6    .045       0
   240.9     .08       0  270.06     .12       0
Bank Sta=225.6,240.9
XS Rating Curve= 0 ,0
Exp/Cntr(USF)=0,0
Exp/Cntr=0.3,0.1

Type RM Length L Ch R = 1 ,7310    ,130.5,129.4,128.5
XS GIS Cut Line= 4
2305353.04471847597779.2428731662305464.43610475597713.718528293
2305599.05884967597660.7033765322305663.98751869597610.666604083
#Sta/Elev= 30
       0 3038.06    19.8 3038.02    30.1 3036.83    40.8 3036.15    59.3 3035.97
    73.2 3035.34   101.1 3035.86     109 3035.66   119.6 3034.44   130.7 3033.76
   146.1 3031.14     159 3030.31   169.5 3031.49   180.5 3031.72   189.1 3032.28
   197.7 3032.36   203.5  3032.2   219.2 3031.04   227.8  3030.8   234.2 3029.73
   239.9 3029.42     245 3029.77   257.9 3032.86   268.2 3034.78   280.1 3035.99
   295.5 3037.17   310.7 3039.28   325.8 3040.49     341 3043.46   355.9 3045.16
#Mann= 3 ,-1,0
       0     .12       0   234.2    .045       0     245     .12       0
Bank Sta=234.2,245
XS Rating Curve= 0 ,0
Exp/Cntr(USF)=0,0
Exp/Cntr=0.3,0.1

Type RM Length L Ch R = 1 ,7181    ,133.5,125.2,113.4
XS GIS Cut Line= 4
2305356.61877364597838.8104594152305485.28475994597837.023431827
2305623.48156004597753.6288110792305692.57996008 597648.19418342
#Sta/Elev= 30
       0 3037.36    35.6 3035.13   115.5 3033.85   141.4 3031.48   164.8 3029.99
   177.3 3030.18   183.4 3030.55   188.1 3030.38   198.1 3029.23  204.77 3027.95
   211.5 3027.36   213.5 3027.95   216.1 3028.72     221 3029.52   235.6 3029.57
   247.2 3029.09   258.2 3029.78   267.6 3029.62   272.2 3029.81   285.1 3031.05
   291.4 3032.05   319.3 3032.96   333.7 3033.01   352.8 3035.88   374.7  3038.7
   381.5 3039.94   391.1 3040.85   395.8  3041.7   405.4 3042.06   416.1 3043.52
#Mann= 3 ,-1,0
       0     .12       0  204.77    .045       0   213.5     .12       0
Bank Sta=204.77,213.5
XS Rating Curve= 0 ,0
Exp/Cntr(USF)=0,0
Exp/Cntr=0.3,0.1

Type RM Length L Ch R = 1 ,7056    ,94.6,95.5,97.1
XS GIS Cut Line= 4
2305659.86215371598064.7379831542305644.33021522597981.176990548
2305648.15547212597760.8224447142305706.55055755597661.485156636
#Sta/Elev= 30
       0 3041.62    48.4  3037.1    68.7 3034.46    72.8 3033.47    76.9 3031.66
    80.9 3030.39    88.8 3029.09     125 3028.26   142.1 3027.48     153 3027.42
     157  3027.1     165 3025.61     169  3026.2     185 3027.04     193  3027.8
     209 3028.29  226.76 3026.68     233 3026.31   239.9 3026.68     253 3027.13
     273 3029.29     293 3031.01   328.2 3032.58   337.4 3032.54   360.6 3036.34
   365.3 3036.87   369.9 3036.91     387 3040.08   393.1 3040.47   420.6 3043.48
#Mann= 4 ,-1,0
       0      .1       0      30     .12       0  226.76    .045       0
   239.9     .12       0
Bank Sta=226.76,239.9
XS Rating Curve= 0 ,0
Exp/Cntr(USF)=0,0
Exp/Cntr=0.3,0.1

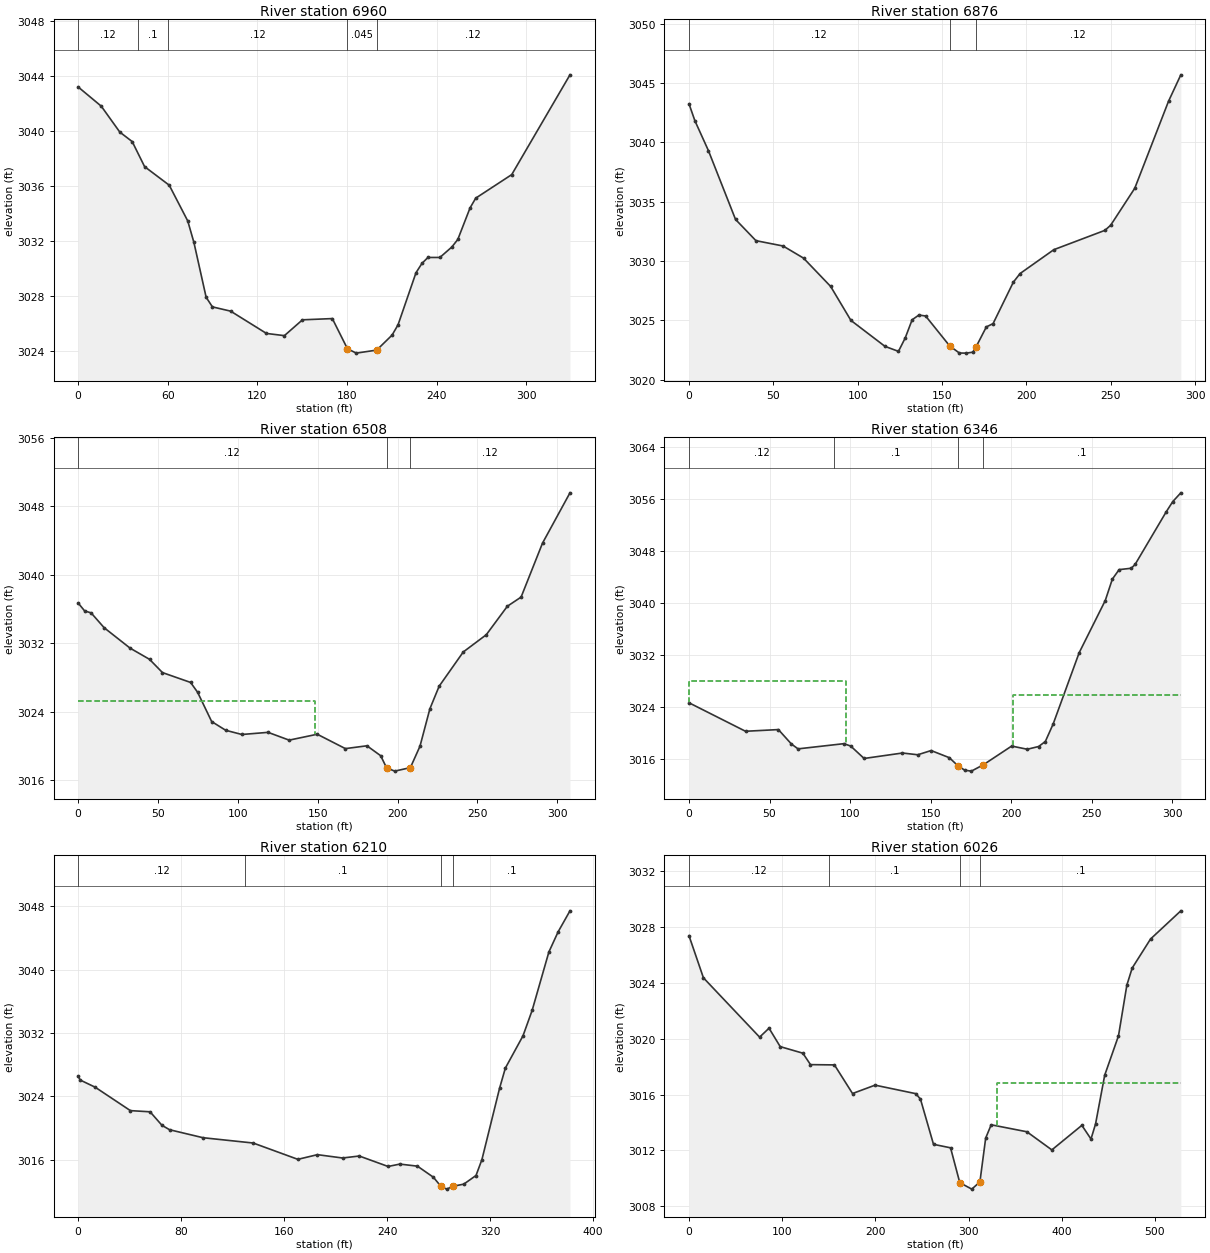
Type RM Length L Ch R = 1 ,6960    ,84.3,84.5,84.7
XS GIS Cut Line= 4
2305764.65673944598000.2386181482305740.23402908 597904.93048015
2305736.06429805 597725.036369682305730.10753942597674.403921369
#Sta/Elev= 30
       0  3043.2    15.5  3041.8    27.9 3039.92    36.2 3039.23    44.5 3037.41
      61 3036.06    73.4 3033.46    77.5 3031.91    85.7 3027.92    89.9 3027.22
   102.1 3026.91   126.1 3025.29   138.1 3025.13   150.2 3026.28   170.2 3026.37
   180.3 3024.18   186.2 3023.86   199.9 3024.08   210.2 3025.17   214.2 3025.92
   226.2  3029.7   230.2 3030.38   234.2 3030.81   242.2 3030.81   250.2 3031.57
   254.2 3032.12   262.4 3034.41   266.2 3035.12   290.3 3036.83   329.3 3044.08
#Mann= 5 ,-1,0
       0     .12       0      40      .1       0      60     .12       0
   180.3    .045       0   199.9     .12       0
Bank Sta=180.3,199.9
XS Rating Curve= 0 ,0
Exp/Cntr(USF)=0,0
Exp/Cntr=0.3,0.1

Type RM Length L Ch R = 1 ,6876    ,371,367.2,359.3
XS GIS Cut Line= 3
2305835.55656719597960.6461135252305820.69429363597825.178915414
2305823.16759038597669.911330654
#Sta/Elev= 30
       0 3043.26     3.5 3041.83    11.5 3039.32    27.6 3033.51    39.7 3031.72
    55.8 3031.27    67.9 3030.25      84 3027.86      96    3025   116.2 3022.81
   124.2 3022.39   128.2 3023.52   132.3 3025.05   136.3 3025.45   140.3 3025.37
   154.63022.841   160.3 3022.25   164.3 3022.24   168.3 3022.32   170.1 3022.74
   176.3 3024.45   180.3 3024.73   192.3 3028.22   196.3 3028.95   216.3 3030.96
   246.6 3032.59     250 3033.02   264.3 3036.14   284.3 3043.47   291.6  3045.7
#Mann= 3 ,-1,0
       0     .12       0   154.6    .045       0   170.1     .12       0
Bank Sta=154.6,170.1
XS Rating Curve= 0 ,0
Exp/Cntr(USF)=0,0
Exp/Cntr=0.3,0.1

Type RM Length L Ch R = 1 ,6508    ,161,162.7,164.8
XS GIS Cut Line= 3
 2306151.2503742597897.186693938 2306141.7195604597844.171542177
2306035.09358101597613.644983396
#Sta/Elev= 30
       0 3036.69     4.1 3035.76     8.1 3035.54    16.3  3033.8    32.5 3031.42
    44.7 3030.11    52.8 3028.56    70.4 3027.41    74.8 3026.26    83.6 3022.84
    92.4 3021.82   102.5 3021.33   118.9 3021.58   132.1 3020.67   149.7 3021.36
   167.3 3019.68   180.8 3020.01   189.4 3018.85   193.13017.428   198.2 3017.05
     208 3017.46     214 3019.96   220.2 3024.33     226 3026.97   241.1 3030.97
   255.5 3032.98   268.7 3036.31   277.3 3037.38   290.7 3043.68   307.9 3049.56
#Mann= 3 ,-1,0
       0     .12       0   193.1    .045       0     208     .12       0
#XS Ineff= 2 , 0
          148.28 3025.24
Permanent Ineff=
       F       F
Bank Sta=193.1,208
XS Rating Curve= 0 ,0
Exp/Cntr(USF)=0,0
Exp/Cntr=0.3,0.1

Type RM Length L Ch R = 1 ,6346    ,138.2,135.6,133.1
XS GIS Cut Line= 3
2306240.84519804597831.7515264552306257.78285515597739.139624139
 2306198.7488788597536.375686494
#Sta/Elev= 30
       0 3024.61    35.1 3020.22    55.5 3020.48    63.6 3018.25    67.7 3017.51
    96.2 3018.31   100.4 3017.94   108.7 3016.03   132.5 3016.87     142  3016.6
   150.3 3017.25   161.6 3016.15     167 3014.89   171.2 3014.22   175.3 3014.08
   182.8 3015.07   200.3 3017.94     210 3017.45     217 3017.87   221.2 3018.64
   226.1 3021.37   242.2 3032.32   258.4 3040.36   262.8 3043.66     267 3045.12
   274.5 3045.33   276.9 3045.91   296.2 3054.01   300.3  3055.6   305.3 3056.95
#Mann= 4 ,-1,0
       0     .12       0      90      .1       0     167    .045       0
   182.8      .1       0
#XS Ineff= 2 , 0
           97.34    3028  201.36         3025.75
Permanent Ineff=
       F       F
Bank Sta=167,182.8
XS Rating Curve= 0 ,0
Exp/Cntr(USF)=0,0
Exp/Cntr=0.3,0.1

Type RM Length L Ch R = 1 ,6210    ,166.4,184.6,201.8
XS GIS Cut Line= 3
2306292.42555361597862.6374939142306379.39422953597654.746617907
2306304.33907086597517.145493673
#Sta/Elev= 30
       0 3026.54     1.6 3026.05    13.2 3025.15    40.6 3022.19    55.9 3022.04
    65.1 3020.34      71 3019.78      97 3018.77     136  3018.1   170.7 3016.04
   185.9 3016.63   205.4 3016.21   218.4 3016.46   240.8 3015.14   249.9 3015.44
   263.6 3015.18     276 3013.78   281.9 3012.62   286.4 3012.28   290.9 3012.63
   299.6 3012.91   309.1    3014   313.7 3016.01   327.4 3025.01   331.9 3027.56
   345.6 3031.63   352.7 3034.84   365.7 3042.21   372.9 3044.76   382.1 3047.41
#Mann= 4 ,-1,0
       0     .12       0     130      .1       0   281.9    .045       0
   290.9      .1       0
Bank Sta=281.9,290.9
XS Rating Curve= 0 ,0
Exp/Cntr(USF)=0,0
Exp/Cntr=0.3,0.1

Type RM Length L Ch R = 1 ,6026    ,258,264.7,274.9
XS GIS Cut Line= 4
 2306299.6735335597865.9967682242306441.92220616597658.186123782
2306466.95858131597652.363914457 2306670.6405382597506.929065419
#Sta/Elev= 30
       0 3027.38    15.5 3024.36    75.8 3020.11    85.9 3020.75    97.9 3019.43
   122.2 3018.96   130.4 3018.14   156.1 3018.12   175.5 3016.07   199.7 3016.67
   243.4 3016.06   248.4 3015.67   262.4 3012.43   280.7 3012.18   290.63009.683
   303.5 3009.22   312.2 3009.74   318.4 3012.88   324.3 3013.83   362.6 3013.33
   389.4 3012.03   421.6 3013.79   431.4 3012.81   436.3 3013.89   446.1 3017.38
   460.9  3020.2   469.9 3023.84   475.6 3025.06   495.3 3027.14   527.8 3029.16
#Mann= 4 ,-1,0
       0     .12       0     150      .1       0   290.6    .045       0
   312.2      .1       0
#XS Ineff= 2 , 0
                          330.25         3016.84
Permanent Ineff=
       F       F
Bank Sta=290.6,312.2
XS Rating Curve= 0 ,0
Exp/Cntr(USF)=0,0
Exp/Cntr=0.3,0.1

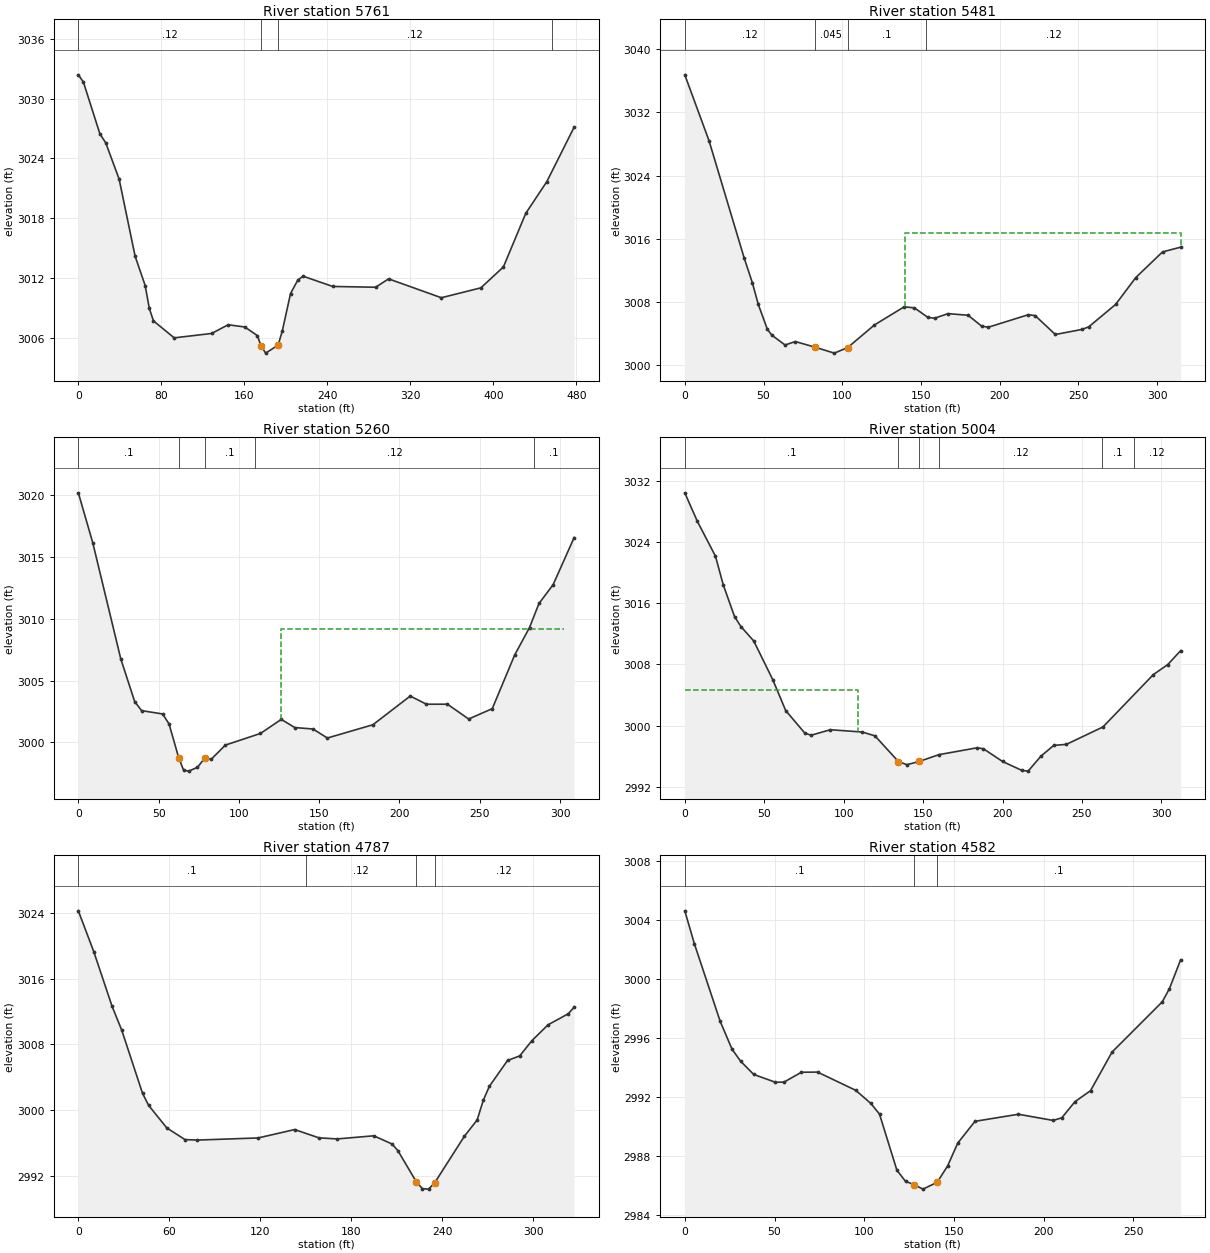
Type RM Length L Ch R = 1 ,5761    ,285.9,279.6,266.2
XS GIS Cut Line= 4
2306387.64878091597903.6602023532306439.08525954597883.343657104
2306599.89013691597878.0722337812306819.70448727597736.219823501
#Sta/Elev= 30
       0 3032.38     4.9 3031.65    20.8 3026.46    26.4 3025.57    39.3 3021.94
    54.7 3014.22    64.4 3011.27    68.4 3008.98    72.4 3007.73    92.4 3006.03
   128.4 3006.47   144.4 3007.34   160.4 3007.12   172.5 3006.26     1763005.245
   180.5  3004.5   192.5  3005.3   196.5  3006.7   204.5 3010.47   211.4  3011.8
   216.5 3012.21   245.1 3011.18   286.5  3011.1     299 3011.94   349.8 3010.05
   387.9 3011.04   409.6 3013.13   431.2 3018.51   451.4 3021.67   477.8 3027.14
#Mann= 4 ,-1,0
       0     .12       0     176    .045       0   192.5     .12       0
  456.19      .1       0
Bank Sta=176,192.5
XS Rating Curve= 0 ,0
Exp/Cntr(USF)=0,0
Exp/Cntr=0.3,0.1

Type RM Length L Ch R = 1 ,5481    ,215.5,220.9,223.3
XS GIS Cut Line= 3
2306579.03719667598137.7512105662306689.72022357598046.705677214
2306850.92225108597987.772246053
#Sta/Elev= 30
       0 3036.77    15.4 3028.42    37.7 3013.58    42.9 3010.45    46.7 3007.68
    52.4 3004.57    55.2 3003.81    63.7 3002.55    70.2 3002.99    82.8 3002.27
      95 3001.52   103.5 3002.23   120.5 3005.09   139.4 3007.39   145.9 3007.25
   154.4 3006.05   158.7 3005.94   167.2 3006.52     180 3006.32   188.5 3004.95
   192.8  3004.8   218.3 3006.39   222.6 3006.27   235.4 3003.88   252.5 3004.53
   256.7 3004.86   273.7 3007.69   286.5 3011.09   303.5 3014.34     315 3014.94
#Mann= 4 ,-1,0
       0     .12       0    82.8    .045       0   103.5      .1       0
  153.32     .12       0
#XS Ineff= 2 , 0
                          139.86          3016.7
Permanent Ineff=
       F       F
Bank Sta=82.8,103.5
XS Rating Curve= 0 ,0
Exp/Cntr(USF)=0,0
Exp/Cntr=0.3,0.1

Type RM Length L Ch R = 1 ,5260    ,251.2,256.1,258.2
XS GIS Cut Line= 4
2306683.90237618598283.0263812512306803.87688599598231.879353382
2306856.39822296598222.7419378432306964.14450532598159.143845745
#Sta/Elev= 30
       0  3020.2       9 3016.15    26.4 3006.77    35.1 3003.29    39.4 3002.56
    52.5 3002.29    56.5 3001.48    62.6  2998.7    65.6 2997.73    68.7 2997.66
    74.2 2997.97    78.6 2998.69    82.9 2998.64    91.6 2999.77   113.4 3000.71
   126.4 3001.85   134.8 3001.19   146.2 3001.07   155.1 3000.34   183.5 3001.42
   206.7 3003.74   216.8 3003.08   229.9 3003.08   243.1 3001.88   257.8 3002.72
   271.7 3007.05     281 3009.29   286.9 3011.24   295.7 3012.76   308.8 3016.58
#Mann= 5 ,-1,0
       0      .1       0    62.6    .045       0    78.6      .1       0
     110     .12       0  283.73      .1       0
#XS Ineff= 1 ,-1
  126.15   302.7 3009.18
Permanent Ineff=
       F
Bank Sta=62.6,78.6
XS Rating Curve= 0 ,0
Exp/Cntr(USF)=0,0
Exp/Cntr=0.3,0.1

Type RM Length L Ch R = 1 ,5004    ,212.1,217.3,215.5
XS GIS Cut Line= 3
2306684.99584935598470.5192850992306936.55707359598447.039639149
2306992.57492025598427.211407778
#Sta/Elev= 30
       0 3030.43     7.8 3026.75    19.3 3022.15    24.2 3018.41    31.3 3014.26
    35.3 3012.96    43.4 3011.07    55.4    3006    63.5 3001.98    75.5 2999.04
    79.5 2998.75    91.6 2999.47   111.7 2999.17   119.7 2998.67   134.52995.303
   139.8  2994.9   147.5 2995.32   159.9 2996.21     184 2997.11     188 2996.98
     200 2995.32   212.1 2994.16   216.1 2994.06   224.1    2996   232.2 2997.42
   240.2 2997.56   263.2 2999.83   294.9 3006.67     304 3007.99   312.1  3009.8
#Mann= 6 ,-1,0
       0      .1       0   134.5    .045       0   147.5      .1       0
     160     .12       0  262.65      .1       0  282.65     .12       0
#XS Ineff= 2 , 0
          109.04  3004.7
Permanent Ineff=
       F       F
Bank Sta=134.5,147.5
XS Rating Curve= 0 ,0
Exp/Cntr(USF)=0,0
Exp/Cntr=0.3,0.1

Type RM Length L Ch R = 1 ,4787    ,197,204.6,208.5
XS GIS Cut Line= 3
 2306694.0362917598613.3605637082306952.73592418598633.096420887
2307020.01581952598629.666470975
#Sta/Elev= 30
       0 3024.24    10.2 3019.26    22.2 3012.64    28.6 3009.72    42.3 3002.04
    46.3 3000.57    58.3 2997.82    70.3  2996.4    78.4 2996.34   118.5  2996.6
   142.6 2997.62   158.6 2996.61   170.6 2996.48   194.7 2996.86   206.8 2995.86
   210.6 2995.06   222.8 2991.25   226.8 2990.42   230.8 2990.37   234.8 2991.12
   254.4 2996.79   262.9  2998.8   266.9 3001.18   270.9 3002.88   282.9 3006.03
   290.9 3006.58   298.9 3008.43   309.6 3010.37     323 3011.72   326.8 3012.53
#Mann= 4 ,-1,0
       0      .1       0     150     .12       0   222.8    .045       0
   234.8     .12       0
Bank Sta=222.8,234.8
XS Rating Curve= 0 ,0
Exp/Cntr(USF)=0,0
Exp/Cntr=0.3,0.1

Type RM Length L Ch R = 1 ,4582    ,217.6,212.7,208.1
XS GIS Cut Line= 3
 2306710.4230573598727.5635123642306884.07037414598845.643687816
2306950.37207693 598848.16946697
#Sta/Elev= 30
       0 3004.64     5.3 3002.42    19.7 2997.15    26.3 2995.26    31.1 2994.44
    38.4 2993.54    50.5 2993.01    55.3 2993.02      65 2993.69      74  2993.7
    95.3 2992.46   103.7 2991.57   108.5 2990.85   118.2 2987.04     123 2986.29
   127.9 2986.06   132.7 2985.76   140.6 2986.22   146.4 2987.32   152.1 2988.88
   161.7 2990.36   185.9 2990.84   205.3 2990.42   210.1  2990.6   217.4 2991.69
   226.1 2992.44   238.1 2995.06   266.1 2998.47   270.1 2999.37   276.3 3001.32
#Mann= 3 ,-1,0
       0      .1       0   127.9    .045       0   140.6      .1       0
Bank Sta=127.9,140.6
XS Rating Curve= 0 ,0
Exp/Cntr(USF)=0,0
Exp/Cntr=0.3,0.1

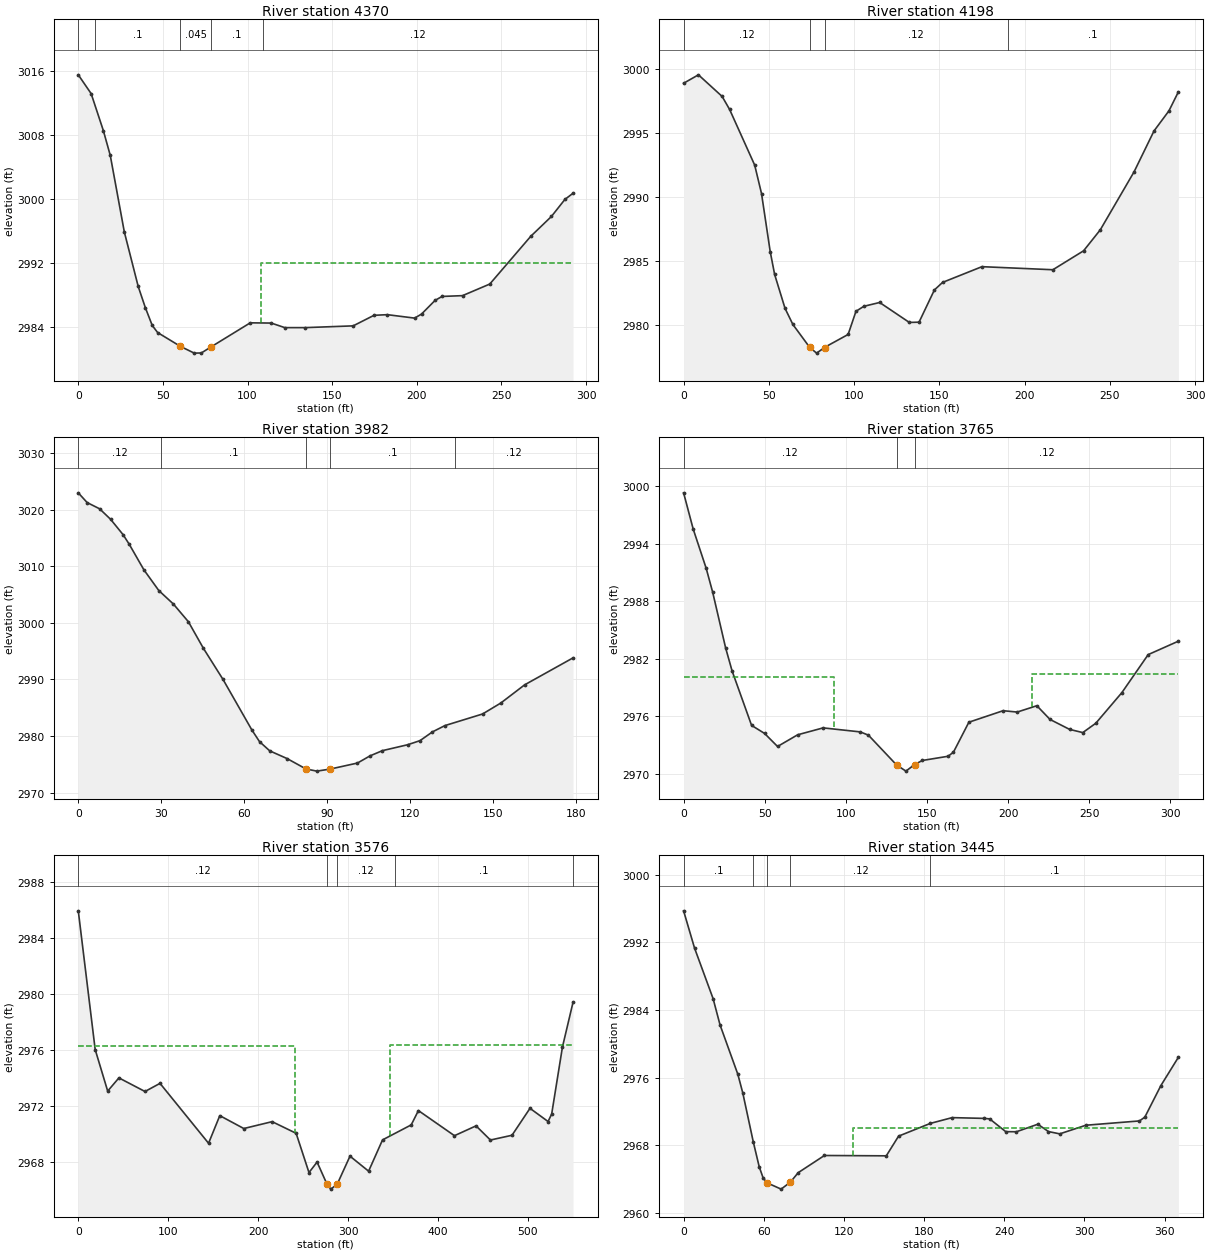
Type RM Length L Ch R = 1 ,4370    ,181.9,171.6,162.2
XS GIS Cut Line= 3
2306637.90436282 598962.115514932306743.37224716598989.921459039
 2306924.8947719598964.982975875
#Sta/Elev= 30
       0 3015.58     7.6 3013.23    14.8 3008.61    18.9  3005.5    27.2 2995.93
    35.4 2989.11    39.6 2986.47    43.7 2984.23    46.9 2983.34    60.3 2981.62
    68.5 2980.77    72.7 2980.79    78.52981.557   101.6 2984.56     114 2984.53
     122 2983.96   134.1 2983.96   162.4 2984.18   174.7  2985.5   182.6 2985.58
   198.7 2985.15   202.8 2985.66   210.8 2987.37   214.9 2987.86     227 2987.96
   243.1 2989.41   267.3 2995.38   279.5 2997.86   287.5    3000   292.3 3000.77
#Mann= 5 ,-1,0
       0     .12       0      10      .1       0    60.3    .045       0
    78.5      .1       0  109.07     .12       0
#XS Ineff= 2 , 0
                          107.83          2992.1
Permanent Ineff=
       F       F
Bank Sta=60.3,78.5
XS Rating Curve= 0 ,0
Exp/Cntr(USF)=0,0
Exp/Cntr=0.3,0.1

Type RM Length L Ch R = 1 ,4198    ,215,215.8,215.7
XS GIS Cut Line= 2
2306676.64633062599174.6024670562306927.83312423 599029.33781533
#Sta/Elev= 30
       0 2998.88     8.7 2999.54    22.6 2997.85      27 2996.83    41.7 2992.48
    45.7 2990.26    50.8 2985.72    53.4 2983.93    59.5 2981.28    64.1 2980.02
    73.9 2978.24      78 2977.78    82.7 2978.22    82.7 2978.23    96.5 2979.24
   101.1 2981.05   105.7 2981.44     115 2981.74   132.4 2980.18   138.1  2980.2
   147.1 2982.72   151.9 2983.31     175 2984.54   216.6  2984.3   234.6 2985.78
   244.4 2987.42   264.2 2991.95   275.9 2995.15   284.7 2996.73   290.2 2998.21
#Mann= 4 ,-1,0
       0     .12       0    73.9    .045       0    82.7     .12       0
     190      .1       0
Bank Sta=73.9,82.7
XS Rating Curve= 0 ,0
Exp/Cntr(USF)=0,0
Exp/Cntr=0.3,0.1

Type RM Length L Ch R = 1 ,3982    ,220.9,216.9,209.9
XS GIS Cut Line= 3
2306833.40449611599342.8911403742306877.36537476599293.569178961
2306977.08151414 599241.03056789
#Sta/Elev= 30
       0 3022.99     3.2 3021.27     7.7 3020.17    11.7  3018.3    16.2 3015.59
    18.4 3013.91    23.7 3009.39    29.1 3005.72    34.4 3003.32    39.8  3000.2
    45.2 2995.52    52.3 2990.01    62.7  2981.1    65.5 2979.01    69.2 2977.38
    75.5 2976.01    82.3 2974.18    86.2  2973.8      91 2974.16   100.9 2975.23
   105.4 2976.49   109.9 2977.42     119 2978.46   123.5 2979.19     128 2980.74
   132.5 2981.85   146.1  2983.9   152.7 2985.84   161.3 2989.05   178.8 2993.82
#Mann= 5 ,-1,0
       0     .12       0      30      .1       0    82.3    .045       0
      91      .1       0  136.07     .12       0
Bank Sta=82.3,91
XS Rating Curve= 0 ,0
Exp/Cntr(USF)=0,0
Exp/Cntr=0.3,0.1

Type RM Length L Ch R = 1 ,3765    ,185.5,189.7,192.5
XS GIS Cut Line= 4
2306854.25152913599503.557948995 2306959.1555828 599500.48890502
2307003.54138454599432.6280805892307018.40225431599314.707266332
#Sta/Elev= 30
       0 2999.29     5.9 2995.52    13.9 2991.43    17.9 2988.94    25.9 2983.12
    29.9 2980.71    41.9 2975.04    49.9  2974.2    57.9 2972.84    70.3 2974.06
      86 2974.78   108.9 2974.36   113.9 2974.02   131.2 2970.92     137 2970.27
   142.4 2970.96   147.1 2971.38     163 2971.82   166.3 2972.25   175.8 2975.37
   196.9 2976.57   205.6 2976.43   217.7 2977.09   225.8 2975.66   237.9 2974.62
     246 2974.29     254 2975.26   270.1 2978.46   286.3 2982.42   304.9 2983.82
#Mann= 3 ,-1,0
       0     .12       0   131.2    .045       0   142.4     .12       0
#XS Ineff= 2 , 0
           92.77 2980.05  214.54          2980.4
Permanent Ineff=
       F       F
Bank Sta=131.2,142.4
XS Rating Curve= 0 ,0
Exp/Cntr(USF)=0,0
Exp/Cntr=0.3,0.1

Type RM Length L Ch R = 1 ,3576    ,148.5,130.7,111.9
XS GIS Cut Line= 4
2306856.72309406 599549.431317432307067.90629556 599609.06776968
2307156.30856595599539.6088429422307147.18769678599321.409588242
#Sta/Elev= 30
       0 2985.93    18.8 2976.04    32.7 2973.08    45.2 2974.02    74.2 2973.05
    90.9 2973.63   144.9 2969.36   157.4 2971.33   184.1 2970.41   215.6  2970.9
   242.3 2970.07   256.6 2967.27   265.6 2968.02   276.5 2966.46   280.8 2966.09
   287.9 2966.43   302.2 2968.44   322.9 2967.37   338.4  2969.6   370.3 2970.67
   378.3 2971.69   418.4  2969.9   442.4  2970.6   458.4 2969.59   482.4 2969.93
   502.4 2971.85   522.5 2970.91   526.5 2971.44   538.5 2976.22   550.3 2979.42
#Mann= 5 ,-1,0
       0     .12       0   276.5    .045       0   287.9     .12       0
  351.87      .1       0  550.26     .12       0
#XS Ineff= 2 , 0
          240.96 2976.31  347.15         2976.37
Permanent Ineff=
       F       F
Bank Sta=276.5,287.9
XS Rating Curve= 0 ,0
Exp/Cntr(USF)=0,0
Exp/Cntr=0.3,0.1

Type RM Length L Ch R = 1 ,3445    ,96.2,94.7,93.1
XS GIS Cut Line= 3
2307254.45363981599672.2661778632307173.21858349599532.676354877
2307163.80942844599324.084809329
#Sta/Elev= 30
       0 2995.74     8.2 2991.33    22.1 2985.34    27.3 2982.23    40.6  2976.4
    44.3 2974.19    52.2 2968.37    56.6 2965.45    59.5 2964.15    62.4 2963.56
      73 2962.81      80 2963.65    85.8 2964.76   105.4 2966.79   151.7 2966.75
   160.9 2969.08   184.7 2970.59     201 2971.27   225.1 2971.18   229.1 2971.12
   241.1 2969.61   249.1  2969.6   265.1 2970.49   273.1 2969.62   281.5 2969.35
   301.1 2970.37   341.2 2970.88   345.2 2971.33   357.2 2975.06   370.3 2978.41
#Mann= 5 ,-1,0
       0      .1       0    52.2     .12       0    62.4    .045       0
      80     .12       0   184.7      .1       0
#XS Ineff= 2 , 0
                          126.55         2970.02
Permanent Ineff=
       F       F
Bank Sta=62.4,80
XS Rating Curve= 0 ,0
Exp/Cntr(USF)=0,0
Exp/Cntr=0.3,0.1