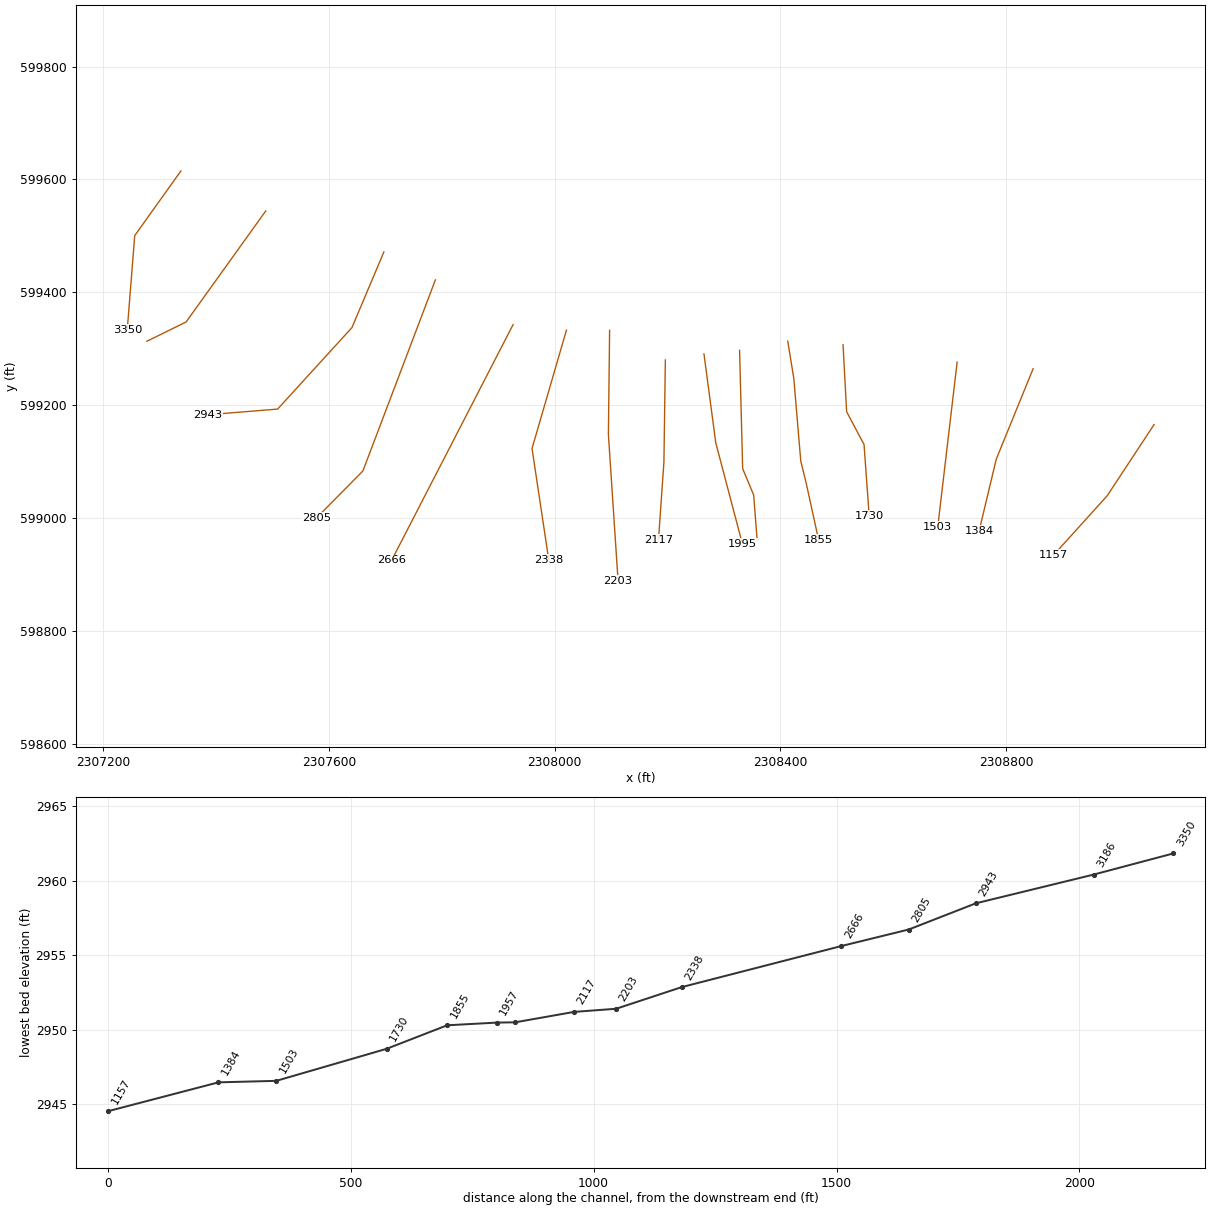
HEC-RAS study OLDRDRN.prj: OLDRDRN

--- OLDRDRN.g01 (geometry) --- (continued)

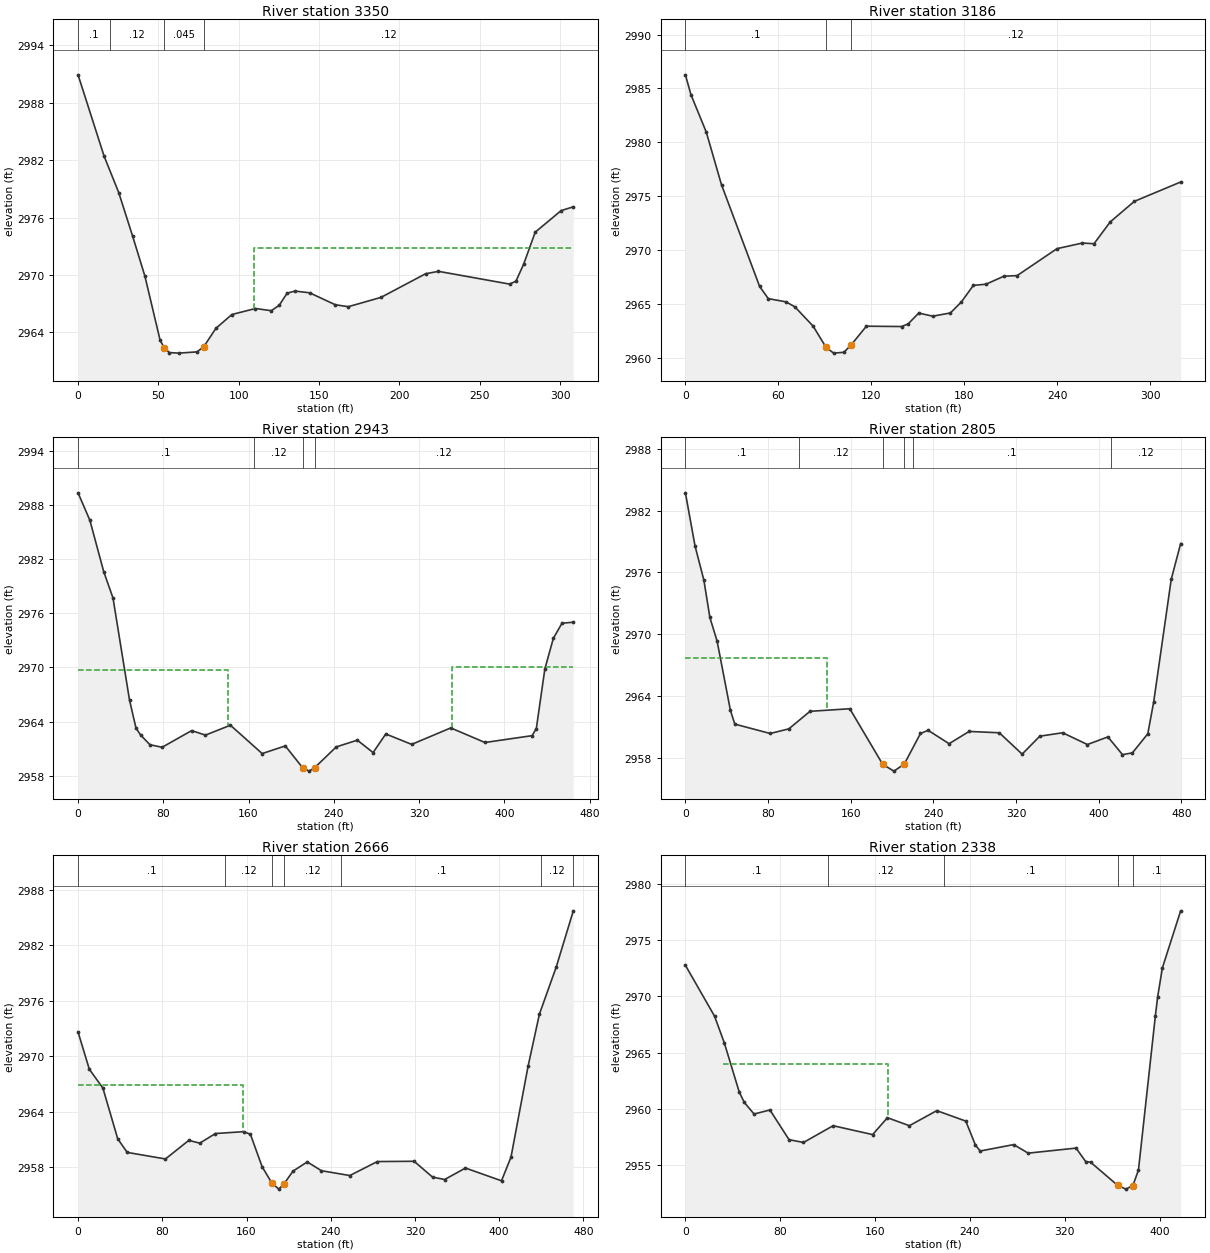
Type RM Length L Ch R = 1 ,3350    ,164.2,164.1,163.9
XS GIS Cut Line= 3
2307337.57963886599615.035238818 2307255.7256848599500.439703127
2307242.47313985599333.613549124
#Sta/Elev= 30
       0  2990.9    16.2 2982.41    25.3 2978.61    33.9 2974.09    41.6 2969.88
    51.1 2963.16    53.6 2962.42    56.8  2961.9    62.6 2961.84      74 2961.97
    78.1 2962.48    85.8 2964.43    95.7 2965.87   110.4  2966.5   120.3 2966.27
   125.2 2966.84   130.1  2968.1     135 2968.32   144.1 2968.14   160.1 2966.89
   168.2 2966.69   188.5 2967.66   216.3 2970.13   224.3 2970.38   268.5 2969.05
   272.5 2969.35   277.3 2971.13   284.5 2974.47   300.6 2976.72   308.2 2977.12
#Mann= 4 ,-1,0
       0      .1       0      20     .12       0    53.6    .045       0
    78.1     .12       0
#XS Ineff= 2 , 0
                          109.64         2972.77
Permanent Ineff=
       F       F
Bank Sta=53.6,78.1
XS Rating Curve= 0 ,0
Exp/Cntr(USF)=0,0
Exp/Cntr=0.3,0.1

Type RM Length L Ch R = 1 ,3186    ,244,242.6,240.4
XS GIS Cut Line= 3
2307487.96304515599544.1097549712307346.80788235599347.348012883
2307277.29965824599313.128579476
#Sta/Elev= 30
       0 2986.26     3.6 2984.41    13.5 2980.93    23.3 2976.05    47.9 2966.61
    53.5 2965.48      65 2965.18    70.7 2964.71    82.4 2962.93    90.8 2960.95
    95.7 2960.42   102.3  2960.5     107 2961.19   116.8 2962.92   139.5 2962.89
   143.7 2963.13   150.6 2964.14   159.6 2963.85     171 2964.15   178.1 2965.17
   185.8 2966.71     194 2966.82   205.5 2967.56   214.1 2967.62   239.8 2970.12
   256.1 2970.64   263.7 2970.58   274.2 2972.61   289.7 2974.51   319.6 2976.31
#Mann= 3 ,-1,0
       0      .1       0    90.8    .045       0     107     .12       0
Bank Sta=90.8,107
XS Rating Curve= 0 ,0
Exp/Cntr(USF)=0,0
Exp/Cntr=0.3,0.1

Type RM Length L Ch R = 1 ,2943    ,133.4,138.3,141.6
XS GIS Cut Line= 4
2307697.29213484599471.389642777 2307640.8086289599337.453242287
2307508.99438143599192.9176042972307385.57734291599182.915358392
#Sta/Elev= 30
       0  2989.4    11.1 2986.35    24.1 2980.64    32.8 2977.72    48.3 2966.38
    54.4 2963.26    58.8 2962.49    67.5 2961.42    78.9 2961.14   106.6 2962.99
   119.6 2962.49     143 2963.59   172.8 2960.44   194.5 2961.29   210.7 2958.88
   216.8 2958.49   222.22958.886   242.3 2961.18   262.1 2961.93   276.9 2960.55
   288.8 2962.62   313.1 2961.46   349.8 2963.29   381.9 2961.67   426.1 2962.43
   430.1 2963.22   438.1 2969.84   446.1 2973.25   454.2 2974.92   464.8 2975.03
#Mann= 4 ,-1,0
       0      .1       0  165.36     .12       0   210.7    .045       0
   222.2     .12       0
#XS Ineff= 2 , 0
          140.28 2969.73  350.99         2970.04
Permanent Ineff=
       F       F
Bank Sta=210.7,222.2
XS Rating Curve= 0 ,0
Exp/Cntr(USF)=0,0
Exp/Cntr=0.3,0.1

Type RM Length L Ch R = 1 ,2805    ,139.7,138.7,136.7
XS GIS Cut Line= 3
2307788.58858587 599421.900408692307660.12806994599083.225886186
2307577.84202672 599000.00331098
#Sta/Elev= 30
       0 2983.72     9.3 2978.58    17.9 2975.24    23.7 2971.63    30.7 2969.33
    43.6 2962.61    47.8 2961.29    82.1 2960.38   100.1 2960.83   120.6 2962.53
   159.1 2962.78     1912957.382   201.8 2956.73   211.8 2957.41   227.5 2960.38
   234.9 2960.69   255.2 2959.39   274.6 2960.58   303.8 2960.45   325.9 2958.38
     343 2960.12   365.1 2960.45   389.1 2959.31   408.9 2960.05     423 2958.33
   432.6  2958.5   447.5 2960.35   453.2 2963.44   470.2 2975.34   479.3  2978.8
#Mann= 6 ,-1,0
       0      .1       0     110     .12       0     191    .045       0
   211.8     .12       0     220      .1       0  412.22     .12       0
#XS Ineff= 2 , 0
           136.9  2967.7
Permanent Ineff=
       F       F
Bank Sta=191,211.8
XS Rating Curve= 0 ,0
Exp/Cntr(USF)=0,0
Exp/Cntr=0.3,0.1

Type RM Length L Ch R = 1 ,2666    ,322.5,328.9,337
XS GIS Cut Line= 2
2307926.37397792599342.7191978992307710.93725011598924.605226486
#Sta/Elev= 30
       0  2972.6    10.7 2968.58    23.6 2966.54    37.7 2961.05    46.7 2959.59
      83 2958.88   105.2 2960.89   115.6 2960.59   130.5 2961.63   157.2 2961.83
   163.7 2961.55   174.8 2958.05   184.1 2956.27   190.7 2955.62   195.8 2956.22
   204.2 2957.57   217.7 2958.56   231.2 2957.61   258.1 2957.09   284.3  2958.6
   319.2 2958.63   336.7 2956.92   348.2 2956.66     368  2957.9   402.2 2956.52
   411.2 2959.07   427.4 2968.88   438.2 2974.53   454.2 2979.63   470.4  2985.7
#Mann= 7 ,-1,0
       0      .1       0     140     .12       0   184.1    .045       0
   195.8     .12       0     250      .1       0     440     .12       0
     470      .1       0
#XS Ineff= 2 , 0
          156.34 2966.92
Permanent Ineff=
       F       F
Bank Sta=184.1,195.8
XS Rating Curve= 0 ,0
Exp/Cntr=0.3,0.1

Type RM Length L Ch R = 1 ,2338    ,136.2,134.7,133.4
XS GIS Cut Line= 3
2308020.89852394599332.7847294152307959.91739054599123.034879207
2307989.51227162598925.955542746
#Sta/Elev= 30
       0 2972.77    24.6 2968.24    32.9 2965.84    45.4  2961.5    49.6 2960.58
    57.9 2959.54    71.3  2959.9    87.4 2957.26    99.6 2957.01   124.6  2958.5
   157.9 2957.71   170.4 2959.21   188.9  2958.5     212 2959.84   236.5 2958.91
   244.6 2956.78   248.6 2956.25   276.9 2956.82   289.1 2956.06   329.5 2956.51
   337.6 2955.31   341.7 2955.26   364.5  2953.2   371.5 2952.86   377.4 2953.18
   382.1 2954.55   396.4 2968.29   398.3 2969.96   402.3 2972.54   417.7 2977.61
#Mann= 5 ,-1,0
       0      .1       0     120     .12       0  218.43      .1       0
   364.5    .045       0   377.4      .1       0
#XS Ineff= 1 ,-1
   31.39   171.12964.026
Permanent Ineff=
       F
Bank Sta=364.5,377.4
XS Rating Curve= 0 ,0
Exp/Cntr(USF)=0,0
Exp/Cntr=0.3,0.1

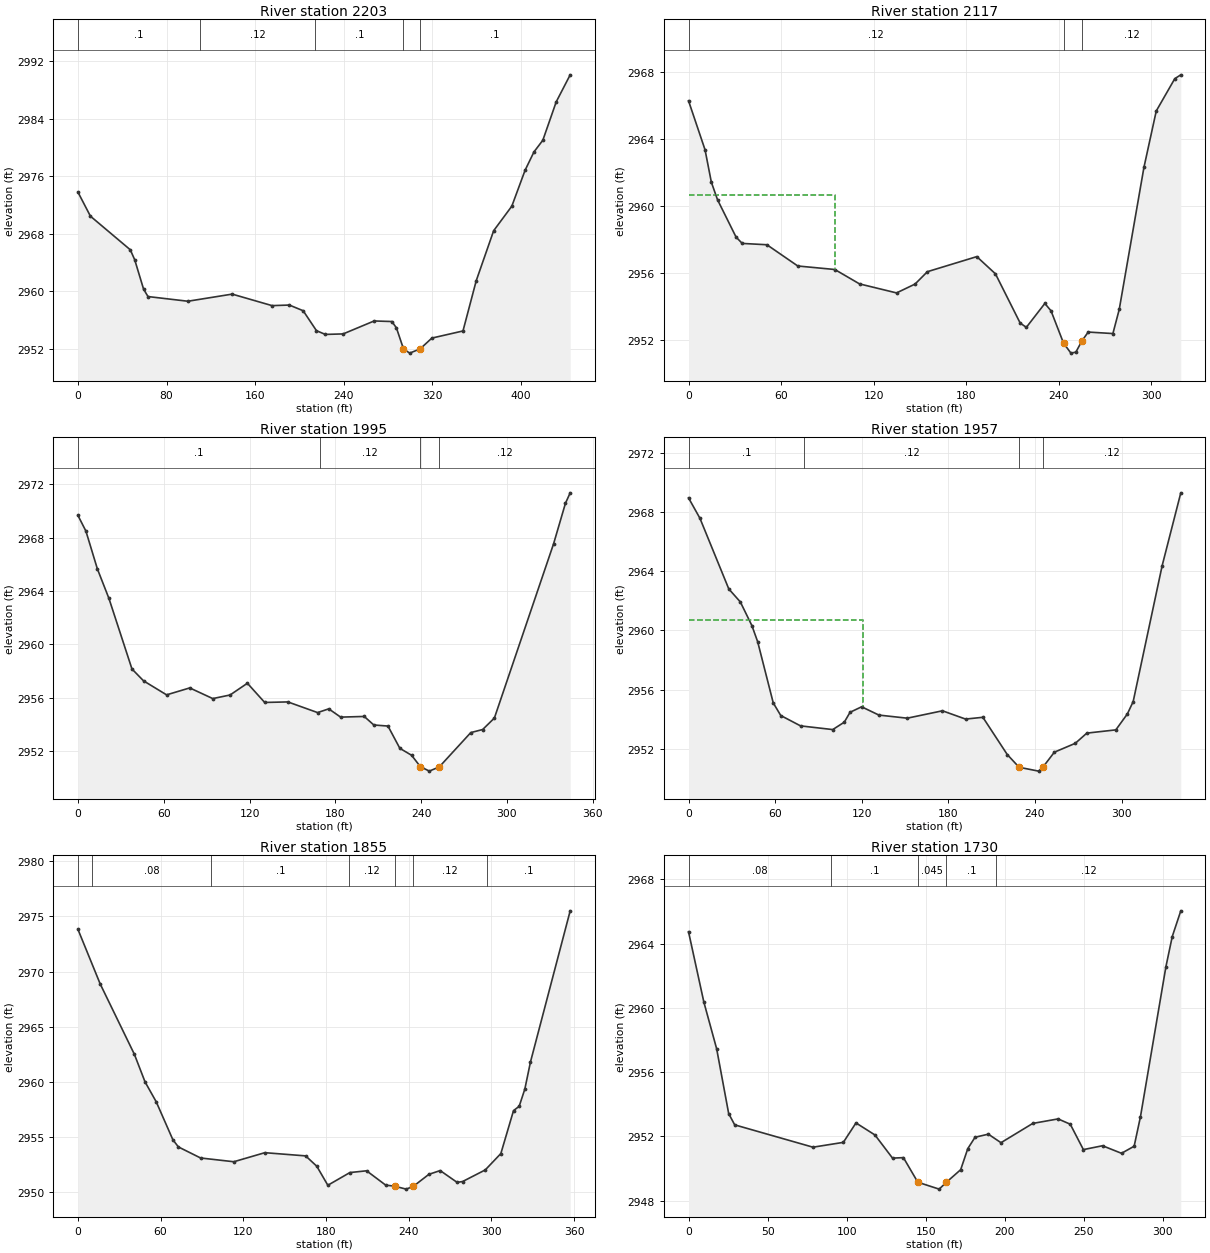
Type RM Length L Ch R = 1 ,2203    ,87.8,86.3,84.6
XS GIS Cut Line= 3
2308097.41350523 599332.500232732308095.26907212599148.078985705
2308112.42453696598888.602580007
#Sta/Elev= 30
       0 2973.79    11.3 2970.44    47.3 2965.77    51.3 2964.38    59.3  2960.3
    63.3 2959.27    99.3 2958.62   139.3 2959.61   175.3 2958.01   190.9 2958.09
   203.4  2957.3   215.4 2954.53   223.4 2954.01   239.5 2954.08   267.5 2955.88
   283.5  2955.8   287.6 2954.92  293.98    2952   299.6 2951.41   309.12952.009
   319.6  2953.5   347.7 2954.49   359.7 2961.49   375.4 2968.42   391.8 2971.83
   403.8 2976.83   411.8 2979.37   419.8 2980.99   431.9 2986.33   444.5 2990.08
#Mann= 5 ,-1,0
       0      .1       0     110     .12       0  214.43      .1       0
  293.98    .045       0   309.1      .1       0
Bank Sta=293.98,309.1
XS Rating Curve= 0 ,0
Exp/Cntr(USF)=0,0
Exp/Cntr=0.3,0.1

Type RM Length L Ch R = 1 ,2117    ,117.9,121.5,125.2
XS GIS Cut Line= 3
2308196.22154861 599279.973381892308193.69325486599099.360770303
2308184.07239218598961.327847075
#Sta/Elev= 30
       0 2966.29    10.7 2963.36    14.8 2961.42    18.8 2960.37    30.8 2958.14
    34.8 2957.76    50.8 2957.68    70.8 2956.41    94.8  2956.2   110.8 2955.34
   134.8  2954.8   146.8 2955.33   154.8 2956.07   186.8 2956.97   198.9 2955.94
   214.9    2953   218.9 2952.74   230.9 2954.17   234.9 2953.73     243  2951.8
   247.8  2951.2     251 2951.26     255 2951.94     259 2952.46     275 2952.37
   279.1 2953.81   295.1  2962.3   303.1 2965.68   315.1 2967.61     319 2967.84
#Mann= 3 ,-1,0
       0     .12       0     243    .045       0     255     .12       0
#XS Ineff= 2 , 0
           94.85 2960.65
Permanent Ineff=
       F       F
Bank Sta=243,255
XS Rating Curve= 0 ,0
Exp/Cntr(USF)=0,0
Exp/Cntr=0.3,0.1

Type RM Length L Ch R = 1 ,1995    ,36.8,38.4,40.1
XS GIS Cut Line= 3
2308264.67928741599290.6837871832308285.58751019 599133.06795397
2308332.76503849598954.007789707
#Sta/Elev= 30
       0 2969.68     5.6  2968.5    13.6 2965.67    21.7 2963.45    37.8 2958.16
    45.9 2957.27      62 2956.22    78.2 2956.74    94.3 2955.94   106.4 2956.21
   118.5 2957.09   130.6 2955.65   146.8 2955.69   167.6 2954.89   175.4 2955.17
   183.7 2954.55   200.2  2954.6   206.9 2953.96   216.8 2953.88   225.1 2952.21
   233.3 2951.69   239.42950.842   245.7  2950.5   252.7 2950.82   274.7 2953.39
     283 2953.62   291.2 2954.48   332.6 2967.55   340.9 2970.59   344.2 2971.37
#Mann= 4 ,-1,0
       0      .1       0     169     .12       0   239.4    .045       0
   252.7     .12       0
Bank Sta=239.4,252.7
XS Rating Curve= 0 ,0
Exp/Cntr(USF)=0,0
Exp/Cntr=0.3,0.1

Type RM Length L Ch R = 1 ,1957    ,104.3,101.7,99.2
XS GIS Cut Line= 4
2308327.80489031599297.0575739592308333.26182058599087.355539257
2308352.75085726599040.581851219  2308358.987349598960.287020088
#Sta/Elev= 30
       0 2968.96     7.9 2967.58    27.9  2962.8    35.9 2961.92    43.9 2960.32
    47.9 2959.23    58.7 2955.09    63.9 2954.24    77.6 2953.54    99.9 2953.29
   107.9 2953.79   111.9 2954.46   119.9 2954.83   131.9 2954.27   151.5 2954.06
   175.9 2954.56   191.9    2954   203.9 2954.12   220.8  2951.6     229 2950.74
   242.5 2950.48   245.5 2950.75   253.4 2951.76   267.9 2952.36   275.9 2953.05
     296 2953.27     304 2954.35     308 2955.18   328.1 2964.38     341  2969.3
#Mann= 4 ,-1,0
       0      .1       0      80     .12       0     229    .045       0
   245.5     .12       0
#XS Ineff= 2 , 0
          120.88  2960.7
Permanent Ineff=
       F       F
Bank Sta=229,245.5
XS Rating Curve= 0 ,0
Exp/Cntr(USF)=0,0
Exp/Cntr=0.3,0.1

Type RM Length L Ch R = 1 ,1855    ,124.3,124.6,128.7
XS GIS Cut Line= 5
2308413.18127993599313.2003347852308423.90344545599247.259016808
2308436.23393581599100.9014573962308446.41999306 599059.08501185
2308467.86432411598960.977197298
#Sta/Elev= 30
       0 2973.83    16.2 2968.87      41  2962.5    48.7 2960.01    56.8 2958.21
    68.9 2954.77    72.9 2954.12      89 2953.12   113.1 2952.78   135.6  2953.6
   165.2 2953.31   173.3 2952.37   181.3 2950.65   197.3  2951.8   209.4 2951.96
   223.3 2950.66   229.7 2950.57   238.1  2950.3   243.2 2950.54   254.6 2951.64
   262.8 2951.98   275.1 2950.91   279.1 2950.99   295.5 2952.04   306.8 2953.52
     316 2957.41   320.1  2957.8   324.2 2959.36   328.3 2961.82   357.1  2975.5
#Mann= 7 ,-1,0
       0      .1       0      10     .08       0   96.81      .1       0
  196.81     .12       0   229.7    .045       0   243.2     .12       0
  296.72      .1       0
Bank Sta=229.7,243.2
XS Rating Curve= 0 ,0
Exp/Cntr(USF)=0,0
Exp/Cntr=0.3,0.1

Type RM Length L Ch R = 1 ,1730    ,232.2,227.1,218.9
XS GIS Cut Line= 4
2308511.18640091 599306.91399328 2308517.5008488599188.342694105
 2308548.3714829599130.1094524982308557.49235207599003.820494796
#Sta/Elev= 30
       0 2964.74     9.7 2960.36    17.8 2957.45    25.4 2953.42    29.2 2952.72
    78.7 2951.33    97.9 2951.63   105.9 2952.84   117.9 2952.09     129 2950.65
   135.9 2950.68     145 2949.15   158.5 2948.72   163.1 2949.15   172.1 2949.93
   176.6 2951.24   181.2 2951.95   189.6 2952.14   197.6 2951.61   217.7 2952.81
   233.7 2953.09   241.4 2952.76   249.7 2951.18   261.8 2951.42   273.8 2950.95
   281.8 2951.39   285.8 2953.23   301.9 2962.57   305.9 2964.44   311.3 2966.04
#Mann= 5 ,-1,0
       0     .08       0      90      .1       0     145    .045       0
   163.1      .1       0  194.65     .12       0
Bank Sta=145,163.1
XS Rating Curve= 0 ,0
Exp/Cntr(USF)=0,0
Exp/Cntr=0.3,0.1

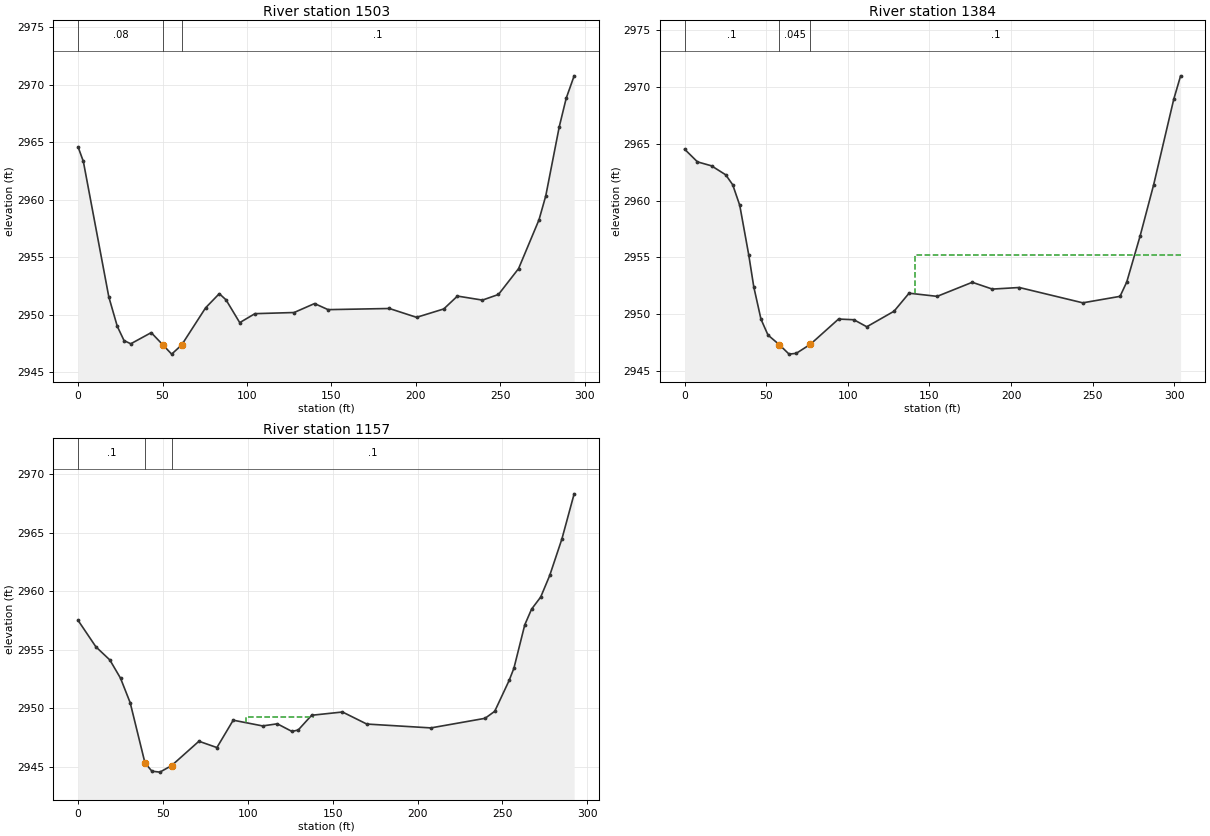
Type RM Length L Ch R = 1 ,1503    ,121.8,118.9,114.2
XS GIS Cut Line= 2
2308713.40191462599276.2088637252308679.09098494598984.565961453
#Sta/Elev= 30
       0 2964.59     3.1 2963.34    18.2 2951.54    23.2 2948.99    27.2 2947.75
    31.2 2947.47    43.3 2948.44    50.3 2947.36    55.4 2946.57    61.32947.363
    75.5  2950.6    83.6 2951.83    87.6 2951.29    95.7 2949.31   104.7 2950.09
   127.9 2950.19     140 2950.97     148 2950.44   184.3 2950.54   200.4 2949.77
   216.5  2950.5   224.6 2951.62   239.4 2951.27   248.9 2951.76   260.8 2954.01
   272.9 2958.26   276.9 2960.34   284.9 2966.36     289 2968.83   293.7 2970.78
#Mann= 3 ,-1,0
       0     .08       0    50.3    .045       0    61.3      .1       0
Bank Sta=50.3,61.3
XS Rating Curve= 0 ,0
Exp/Cntr(USF)=0,0
Exp/Cntr=0.3,0.1

Type RM Length L Ch R = 1 ,1384    ,230.3,227.7,225.4
XS GIS Cut Line= 3
2308848.07855803599264.4761771522308782.74483796599104.214074494
2308752.41039054598977.088925024
#Sta/Elev= 30
       0 2964.53     7.9 2963.41    16.5 2963.06    25.2 2962.27    29.5 2961.39
    33.8 2959.58    39.3 2955.22    42.4 2952.39    46.8 2949.55    51.1 2948.15
   58.13 2947.29      64 2946.47    68.4 2946.54      77 2947.33    94.3 2949.56
   103.7  2949.5   111.6 2948.88   128.3 2950.25   137.5 2951.84   154.7 2951.56
   176.2  2952.8   188.5  2952.2     205 2952.34   243.9 2950.99   266.7 2951.56
   270.8 2952.82     279 2956.88   287.3  2961.4   299.6 2968.93   303.8 2970.99
#Mann= 3 ,-1,0
       0      .1       0   58.13    .045       0      77      .1       0
#XS Ineff= 2 , 0
                          141.38         2955.18
Permanent Ineff=
       F       F
Bank Sta=58.13,77
XS Rating Curve= 0 ,0
Exp/Cntr(USF)=0,0
Exp/Cntr=0.3,0.1

Type RM Length L Ch R = 1 ,1157    ,258.5,256.3,254.1
XS GIS Cut Line= 3
2309062.45796153599165.4718708062308979.31161964599039.249005629
2308884.66363254598934.529981469
#Sta/Elev= 30
       0  2957.5    10.5 2955.24    18.7 2954.12      25 2952.56    30.7 2950.46
    39.4 2945.32    43.5 2944.61    48.2 2944.53    55.12945.088    71.2 2947.17
    81.8 2946.63    91.4 2948.97   108.7 2948.48   117.4 2948.66     126 2948.01
   129.7 2948.13   137.6 2949.39   155.8 2949.67   170.1 2948.64   207.9 2948.31
   239.8 2949.13   245.5 2949.73     254 2952.37   256.8 2953.41   263.2 2957.12
   267.2 2958.46   272.6  2959.5   277.9 2961.34   285.1 2964.47   292.3 2968.32
#Mann= 3 ,-1,0
       0      .1       0    39.4    .045       0    55.1      .1       0
#XS Ineff= 2 ,-1
   98.87  138.76  2949.2  157.19   248.82949.315
Permanent Ineff=
       F       F
Bank Sta=39.4,55.1
XS Rating Curve= 0 ,0
Exp/Cntr(USF)=0,0
Exp/Cntr=0.3,0.1