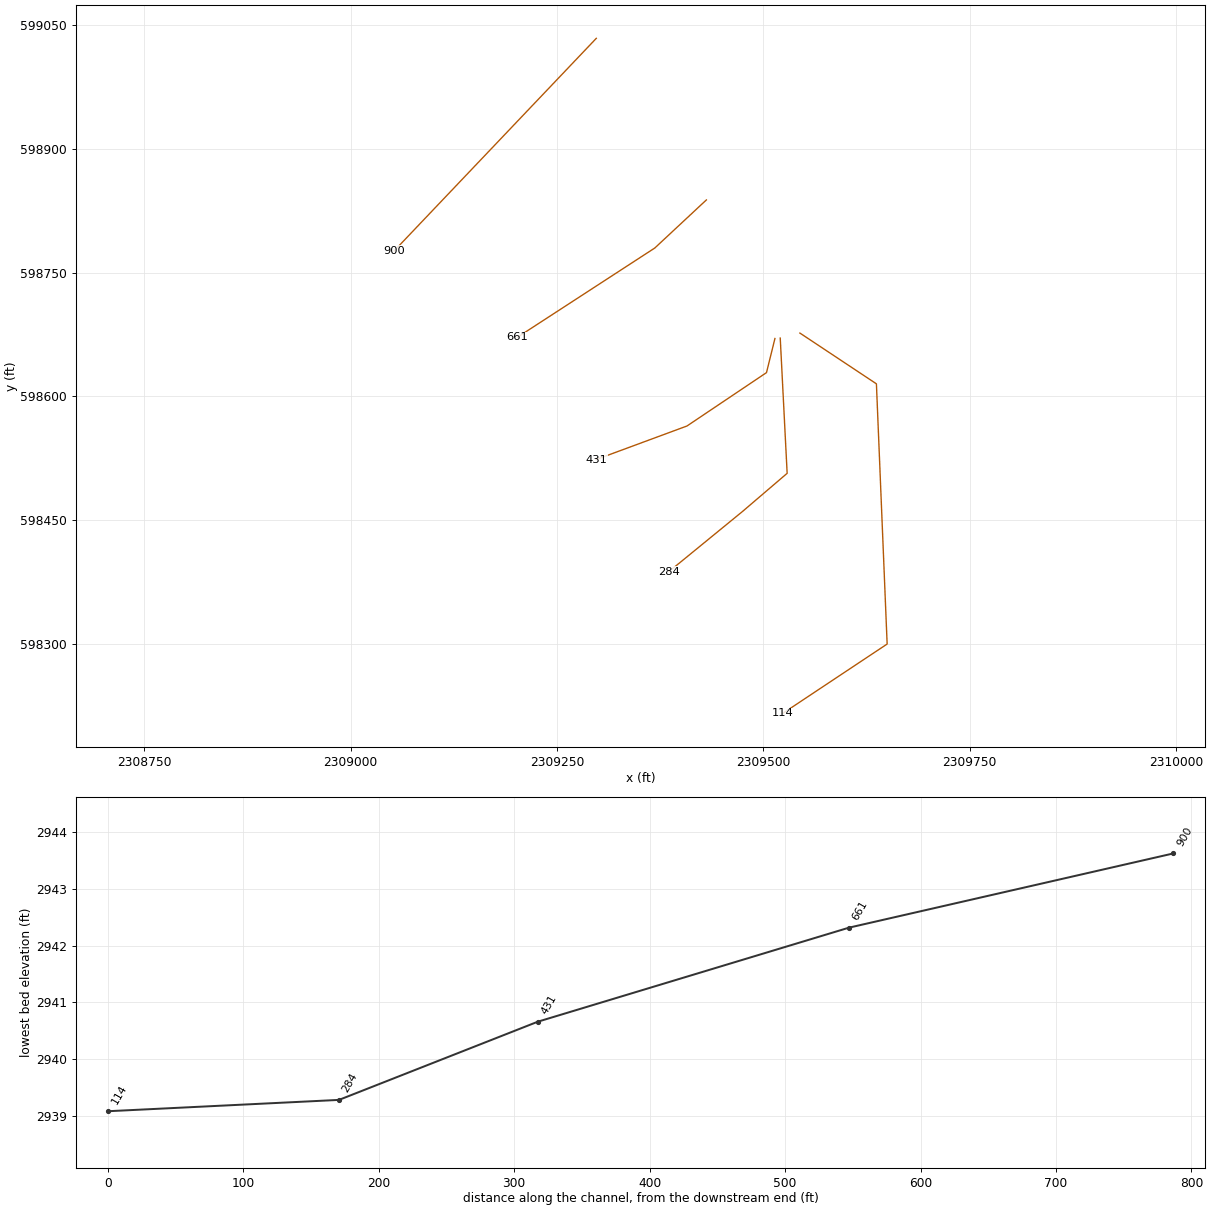
HEC-RAS study OLDRDRN.prj: OLDRDRN

--- OLDRDRN.g01 (geometry) --- (continued)

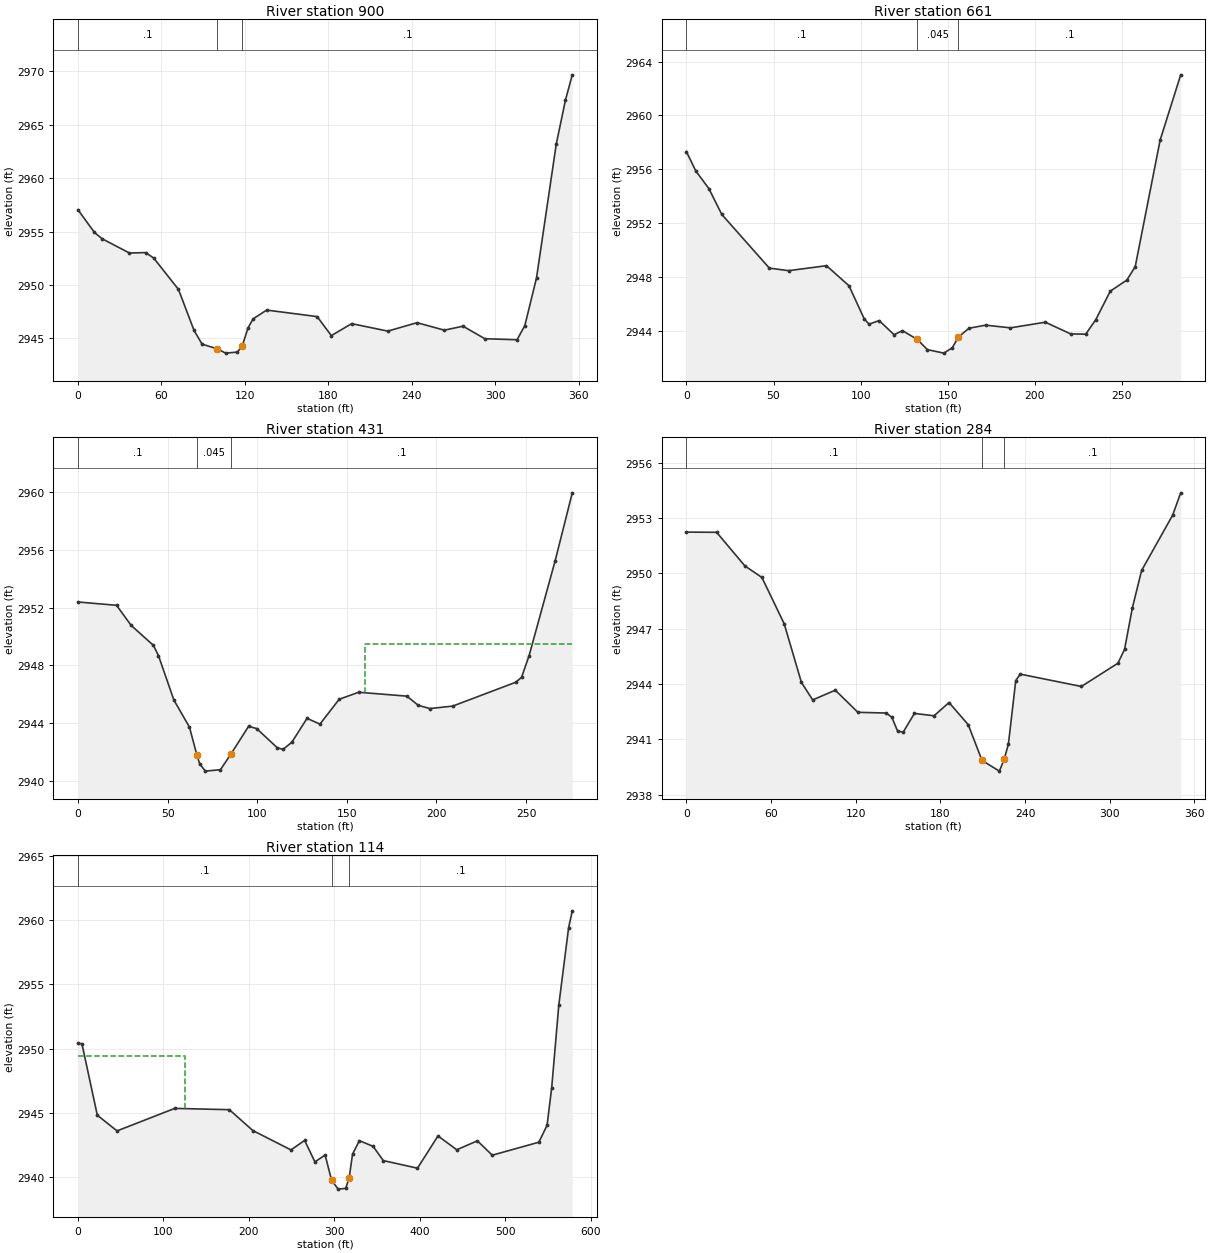
Type RM Length L Ch R = 1 ,900     ,240.6,239.5,235.6
XS GIS Cut Line= 2
2309297.64128056599033.7591557562309052.78102368598776.270003109
#Sta/Elev= 30
       0 2957.04    11.8 2954.93    17.4 2954.33      37    2953    48.6 2953.04
    54.4 2952.53    72.2  2949.6    83.4 2945.76    89.2 2944.47   100.2 2944.03
   106.1 2943.63   114.6 2943.73   118.2 2944.34   122.2 2945.99   125.9 2946.84
   135.6 2947.66   171.9 2947.05   182.1 2945.27   196.7 2946.39   222.7 2945.69
   243.7 2946.48   263.3 2945.78   276.8 2946.15   292.4 2944.98   315.6 2944.88
   321.2 2946.21   329.6 2950.68   343.8 2963.21   350.4 2967.32   355.3 2969.68
#Mann= 3 ,-1,0
       0      .1       0   100.2    .045       0   118.2      .1       0
Bank Sta=100.2,118.2
XS Rating Curve= 0 ,0
Exp/Cntr(USF)=0,0
Exp/Cntr=0.3,0.1

Type RM Length L Ch R = 1 ,661     ,226.2,229.8,228.4
XS GIS Cut Line= 3
2309430.99558884598837.9537398962309368.55271531 598779.72049829
2309202.27225433598671.673278923
#Sta/Elev= 30
       0  2957.3     5.4 2955.86    12.9 2954.55    20.3 2952.63    47.6 2948.64
    58.6 2948.45    80.4 2948.82    93.3 2947.33     102 2944.88   104.8 2944.47
   110.6 2944.74   119.2 2943.69     124 2943.99   132.5 2943.34   138.3 2942.58
   147.8 2942.32   152.6 2942.72   156.1 2943.52   162.2 2944.17   171.7  2944.4
     186  2944.2     206 2944.62   220.5 2943.75   229.2 2943.73     235 2944.82
   243.3 2946.93   252.8 2947.75   257.6 2948.75   271.9 2958.16   283.7 2963.01
#Mann= 3 ,-1,0
       0      .1       0   132.5    .045       0   156.1      .1       0
Bank Sta=132.5,156.1
XS Rating Curve= 0 ,0
Exp/Cntr(USF)=0,0
Exp/Cntr=0.3,0.1

Type RM Length L Ch R = 1 ,431     ,145.5,146.8,146.4
XS GIS Cut Line= 4
2309514.07804539598670.037572658 2309503.8498534598628.719473697
2309407.52545258598564.0447200642309297.60941716598523.433243117
#Sta/Elev= 30
       0 2952.39    21.5 2952.16    29.7 2950.76    42.1 2949.38    44.9 2948.67
    53.5 2945.59    62.2 2943.71    66.3 2941.79    67.9 2941.16    71.1 2940.66
    79.5 2940.76    85.2 2941.82    95.2 2943.77    99.7 2943.61   111.2 2942.28
   114.4 2942.17   119.3 2942.66   127.8 2944.32     135 2943.92   145.7 2945.64
   156.6 2946.13   183.5 2945.86   189.9 2945.22   196.3    2945   209.1 2945.17
   244.4 2946.83   247.5 2947.17   251.7 2948.67   266.2 2955.23   275.8 2959.96
#Mann= 3 ,-1,0
       0      .1       0    66.3    .045       0    85.2      .1       0
#XS Ineff= 2 , 0
                          160.06         2949.45
Permanent Ineff=
       F       F
Bank Sta=66.3,85.2
XS Rating Curve= 0 ,0
Exp/Cntr(USF)=0,0
Exp/Cntr=0.3,0.1

Type RM Length L Ch R = 1 ,284     ,157.7,170.6,182.6
XS GIS Cut Line= 4
2309520.50682896598670.5694068152309528.87412205598506.688262802
2309474.59932033598460.3043554982309385.72931306598387.692535717
#Sta/Elev= 30
       0 2952.24    21.4 2952.23    41.4 2950.41    53.5 2949.78    69.3 2947.27
    81.5 2944.09    89.5 2943.14   105.5 2943.67   121.5 2942.47   141.6 2942.43
   145.6  2942.2   149.6 2941.46   153.6 2941.39   161.6 2942.41   175.5 2942.28
   186.1    2943   199.7  2941.8   209.5 2939.86   221.8 2939.28   225.2 2939.92
   228.2 2940.75   233.4 2944.19   236.6 2944.54   279.9 2943.87   305.8 2945.13
   310.5 2945.88   316.1 2948.15   322.6 2950.16   344.6 2953.16   350.3 2954.37
#Mann= 3 ,-1,0
       0      .1       0   209.5    .045       0   225.2      .1       0
Bank Sta=209.5,225.2
XS Rating Curve= 0 ,0
Exp/Cntr(USF)=0,0
Exp/Cntr=0.3,0.1

Type RM Length L Ch R = 1 ,114     ,,,
XS GIS Cut Line= 4
2309544.34556146598676.6326626722309637.02675813598615.133924696
2309650.01944925598299.8446201472309523.55725567598215.825217561
#Sta/Elev= 30
       0 2950.42     4.6 2950.39    22.6 2944.83    45.7 2943.61   113.2 2945.36
   177.2 2945.26   204.6 2943.64   249.3 2942.13   265.3 2942.87   277.3  2941.2
   289.3 2941.73   296.8 2939.78   304.5 2939.08   313.4 2939.14   317.4 2939.96
   321.4 2941.81   329.4 2942.85   345.4 2942.41   357.4  2941.3   397.4 2940.71
   421.4 2943.22   443.4 2942.14   467.5 2942.84   484.9 2941.72   539.5 2942.73
   549.1 2944.05   554.5 2946.97   562.8 2953.39   574.3 2959.42   578.6 2960.73
#Mann= 3 ,-1,0
       0      .1       0   296.8    .045       0   317.4      .1       0
#XS Ineff= 2 , 0
          125.41 2949.47
Permanent Ineff=
       F       F
Bank Sta=296.8,317.4
XS Rating Curve= 0 ,0
Exp/Cntr(USF)=0,0
Exp/Cntr=0.3,0.1
LCMann Table=0

Chan Stop Cuts=-1
Use User Specified Reach Order=0
Composite Channel Slope=5